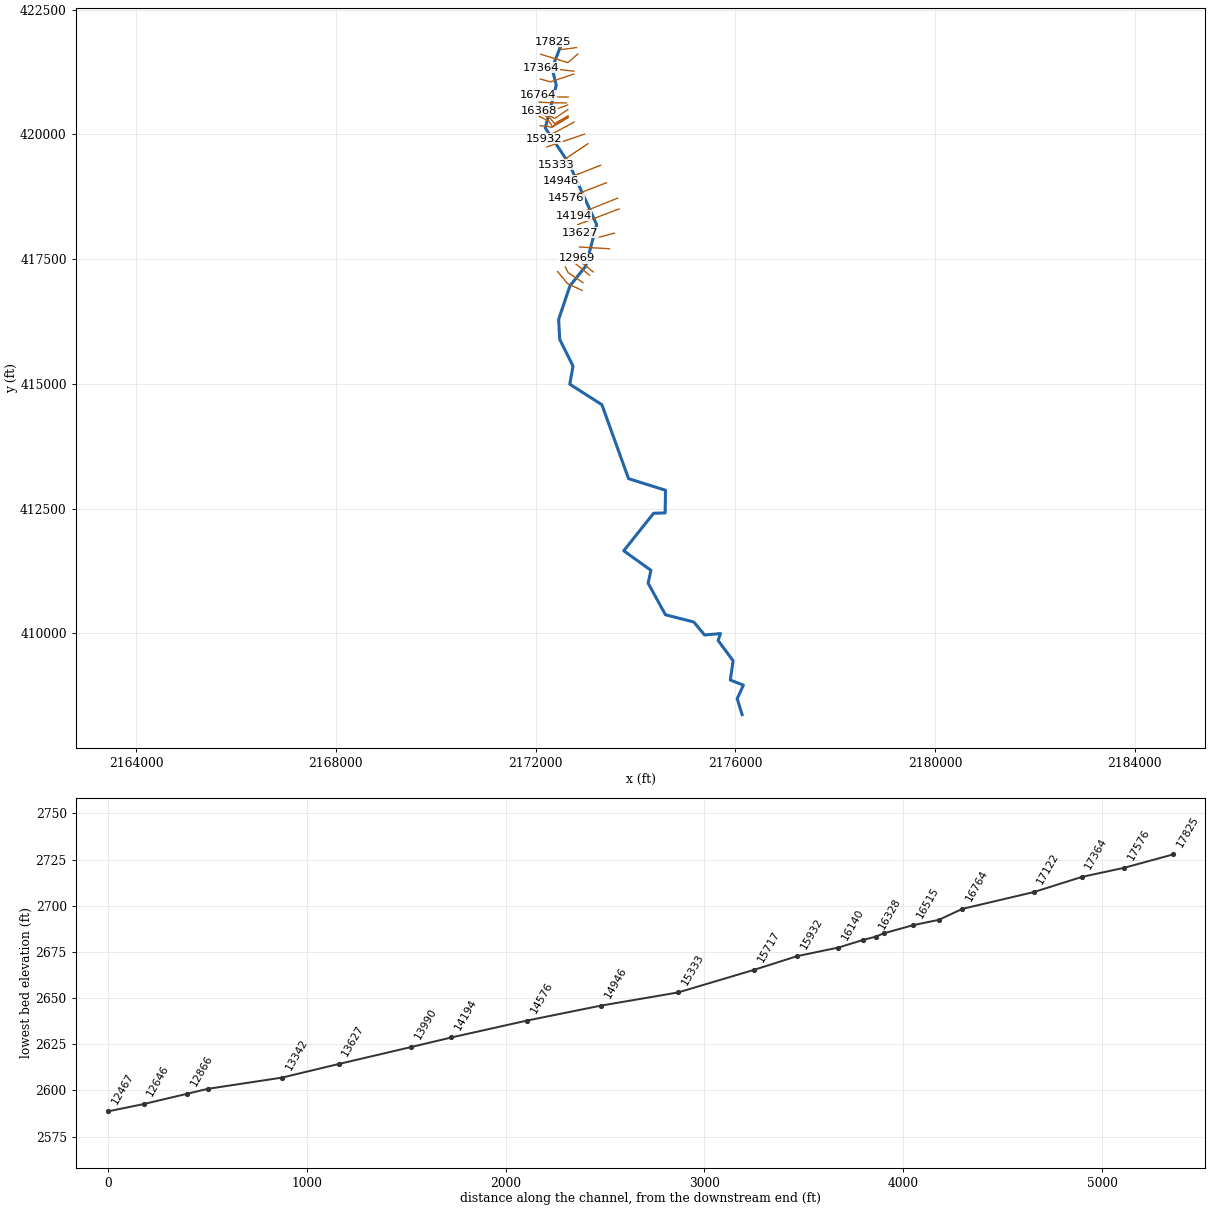
--- BRFFYCK.prj (project) ---

Proj Title=BRFFYCK
Current Plan=p01
Default Exp/Contr=0.3,0.1
English Units
Geom File=g01
Flow File=f01
Plan File=p01
Y Axis Title=Elevation
X Axis Title(PF)=Main Channel Distance
X Axis Title(XS)=Station
BEGIN DESCRIPTION:
----------MODEL BY WOOD PLC 2021----------
Stream Name: Bruffrey Creek
Flood Zone: Approximate
Pocahontas County, WV
HEC-RAS Version: RAS 6.1
Vertical Datum: NAVD88
Projection: NAD 1983 StatePlane West Virginia S FIPS 4702 (US Feet)
Terrain: 1-meter LIDAR (FEMA Region III 3DEP collected 2016-2018)
Land Use: 2019 NLCD
Hydrologic Method:
WV SIR2010-5033 regression equations
END DESCRIPTION:
DSS Export Rating Curves= 0
DSS Export Rating Curve Sorted= 0
DSS Export Volume Flow Curves= 0
DXF OffsetX= 0
DXF OffsetY= 0
DXF ScaleX= 1
DXF ScaleY= 10

--- BRFFYCK.p01 (plan) ---

Plan Title=Floodplain
Program Version=6.00
Short Identifier=Floodplain
Geom File=g01
Flow File=f01
Subcritical Flow
K Sum by GR= 0
Std Step Tol= 0.01
Critical Tol= 0.01
Num of Std Step Trials= 20
Max Error Tol= 0.3
Flow Tol Ratio= 0.001
Split Flow NTrial= 30
Split Flow Tol= 0.02
Split Flow Ratio= 0.02
Log Output Level= 0
Friction Slope Method= 1
Unsteady Friction Slope Method= 2
Unsteady Bridges Friction Slope Method= 1
Parabolic Critical Depth
Global Vel Dist= 0 , 0 , 0
Global Log Level= 0
CheckData=False
Encroach Param=-1 ,0,0, 0
Mapping Interval=1HOUR
Computation Time Step Use Courant=        0
Computation Time Step Use Time Series=    0
Computation Time Step Count To Double=0
Computation Time Step Max Doubling=0
Computation Time Step Max Halving=0
Computation Time Step Residence Courant=0
Run HTab= 0
Run UNet= 0
Run Sediment= 0
Run PostProcess= 0
Run WQNet= 0
Run RASMapper=-1
UNET Theta= 0
UNET Theta Warmup= 0
UNET ZTol= 0
UNET ZSATol= 0
UNET MxIter= 0
UNET Max Iter WO Improvement= 0
UNET MaxInSteps= 0
UNET DtIC= 0
UNET DtMin= 0
UNET MaxCRTS= 0
UNET WFStab= 0
UNET SFStab= 0
UNET WFX= 1
UNET SFX= 1
UNET Gravity=32.174
UNET 1D Methodology=Finite Difference
UNET DSS MLevel= 1
UNET Pardiso=0
UNET DZMax Abort= 0
UNET Use Existing IB Tables= 0
UNET Froude Reduction=False
UNET Froude Limit= 0
UNET Froude Power= 0
UNET D1 Cores= 0
UNET WindReference=Eulerian
UNET WindDragFormulation=Hsu (1988)
UNET D2 Coriolis=0
UNET D2 Cores= 0
UNET D2 Theta= 1
UNET D2 Theta Warmup= 1
UNET D2 Z Tol= 0.01
UNET D2 Volume Tol= 0.01
UNET D2 Max Iterations= 20
UNET D2 Equation= 0
UNET D2 RampUpFraction=0.1
UNET D2 TimeSlices= 1
UNET D2 Turbulence Formulation=Non-Conservative (original)
UNET D2 Eddy Viscosity=0.3
UNET D2 Transverse Eddy Viscosity=0.1
UNET D2 Smagorinsky Mixing=0
UNET D2 BCVolumeCheck=0
UNET D2 Cores=0
UNET D2 SolverType=PARDISO (Direct)
UNET D2 Minimum Iterations= 2147483647
UNET D2 Maximum Iterations= 2147483647
UNET D2 Restart Number= 10
UNET D2 Relaxation Coeff=1.3
UNET D2 SOR Precondition Iterations= 10
UNET D2 ILUT Maximum Fill= 8
UNET D2 ILUT Tolerance=1E-08
UNET D1D2 MaxIter= 0
UNET D1D2 ZTol=0.01
UNET D1D2 QTol=0.1
UNET D1D2 MinQTol=1
Write IC File= 0
Write IC File at Fixed DateTime=0
Write IC File at Sim End=0
Echo Input=False
Echo Parameters=False
Echo Output=False
Write Detailed= 0
HDF Write Warmup=0
HDF Write Time Slices=0
HDF Flush=0
HDF Compression= 1
HDF Chunk Size= 1
HDF Spatial Parts= 1
HDF Use Max Rows=0
HDF Fixed Rows= 1
Calibration Method= 0
Calibration Iterations= 20
Calibration Max Change=0.05
Calibration Tolerance=0.2
Calibration Maximum=1.5
Calibration Minimum=0.5
Calibration Optimization Method= 1
WQ AD Non Conservative
WQ ULTIMATE=-1
WQ Max Comp Step=1HOUR
WQ Output Interval=15MIN
WQ Output Selected Increments= 0
WQ Output face flow=0
WQ Output face velocity=0
WQ Output face area=0
WQ Output face dispersion=0
WQ Output cell volume=0
WQ Output cell surface area=0
WQ Output cell continuity=0
WQ Output cumulative cell continuity=0
WQ Output face conc=0
WQ Output face dconc_dx=0
WQ Output face courant=0
WQ Output face peclet=0
WQ Output face adv mass=0
WQ Output face disp mass=0
WQ Output cell mass=0
WQ Output cell source sink temp=0
WQ Output nsm pathways=0
WQ Output nsm derived pathways=0
WQ Create Restart=0
WQ Fixed Restart=0
WQ System Summary=0
WQ Write To DSS=0
Sorting and Armoring Iterations= 10
XS Update Threshold= 0.02
Bed Roughness Predictor= 0
Hydraulics Update Threshold= 0.02
Energy Slope Method= 1
Volume Change Method= 1
Sediment Retention Method= 0
Sediment TS Multiplier= 1
Warm Up Method= 0
XS Weighting Method= 0
Number of US Weighted Cross Sections= 1
Number of DS Weighted Cross Sections= 1
Upstream XS Weight=0
Main XS Weight=1
Downstream XS Weight=0
Number of DS XS's Weighted with US Boundary= 1
Upstream Boundary Weight= 1
Weight of XSs Associated with US Boundary= 0
Number of US XS's Weighted with DS Boundary= 1
Downstream Boundary Weight= 0.5
Weight of XSs Associated with DS Boundary= 0.5
Percentile Method= 0
Sediment Output Level= 3
Mass or Volume Output= 0
Output Increment Type= 1
Profile and TS Output Increment= 1
Transport Output Increment 1
XS Output Flag= 0
XS Output Increment= 10
Read HDF5 Sediment Hotstart= 0
Sediment Hotstart Type= 0
Write Gradation File= 0
Read Gradation Hotstart= 0
Write HDF5 File= 1
Write Binary Output= 1
Write DSS Sediment File= 0
DSS Sediment Output Type= 1
SV Curve= 0
Specific Gage Flag= 0
Subcell Erosion Methods= 0
Subcell Deposition Methods= 0
Advection Scheme= 1
Matrix Solver= 0
Implicit Weighting Factor= 1
Maximum Outer Loop Convergence Iterations= 5
Convergence Maximum Absolute= 0.001
Convergence RMSE= 0.0001
Grain Fractions Max Abs Error= 0.001
Max Subgrid Regions= 1
Max Subgrid Length Scale= 3.402823E+38
Initial Layer Thickness= 3.402823E+38
Min Layer Thickness= 3.402823E+38
Max Layer Thickness= 3.402823E+38
Number of Layers= 5

--- BRFFYCK.f01 (steady flow) ---

Flow Title=Flow
Program Version=6.10
Number of Profiles= 6
Profile Names=01pct,10pct,04pct,02pct,0_2pct,01plus
River Rch & RM=BRFFYCK,Main            ,17825
     731     390     516     620    1020    1080
River Rch & RM=BRFFYCK,Main            ,16645
     886     476     628     753    1230    1310
River Rch & RM=BRFFYCK,Main            ,6789
    1290     701     919    1100    1770    1900
Boundary for River Rch & Prof#=BRFFYCK,Main            , 1
Up Type= 0
Dn Type= 3
Dn Slope=0.06016
Boundary for River Rch & Prof#=BRFFYCK,Main            , 2
Up Type= 0
Dn Type= 3
Dn Slope=0.06016
Boundary for River Rch & Prof#=BRFFYCK,Main            , 3
Up Type= 0
Dn Type= 3
Dn Slope=0.06016
Boundary for River Rch & Prof#=BRFFYCK,Main            , 4
Up Type= 0
Dn Type= 3
Dn Slope=0.06016
Boundary for River Rch & Prof#=BRFFYCK,Main            , 5
Up Type= 0
Dn Type= 3
Dn Slope=0.06016
Boundary for River Rch & Prof#=BRFFYCK,Main            , 6
Up Type= 0
Dn Type= 3
Dn Slope=0.06016
DSS Import GetInterval= 0
DSS Import GetPeak= 0
DSS Import FillOption= 0

--- BRFFYCK.g01 (geometry) ---

Geom Title=Geometry
Program Version=6.10

River Reach=BRFFYCK         ,Main
Reach XY= 30
     2172498.668       421751.92 2172330.5562455421327.244959442
     2172414.435      420985.491     2172194.975      420128.385
     2172667.603      419420.473     2173223.926      418191.671
     2173006.462      417360.235     2172688.079      416960.947
     2172462.934      416290.588     2172484.454      415891.814
      2172750.41      415357.208     2172686.128      414993.549
     2173329.225      414581.598     2173863.339      413100.105
2174603.22067493412868.3110590682174596.24658504412413.822425948
     2174365.555       412406.57     2173766.472      411655.378
     2174311.301      411263.775      2174255.16      411006.872
     2174602.164      410372.872     2175170.388      410227.523
     2175386.484      409967.512     2175705.124      409996.988
     2175656.706      409858.715     2175958.157       409450.48
      2175901.31      409064.537     2176163.488      408962.967
     2176039.819      408690.822      2176137.31      408372.531

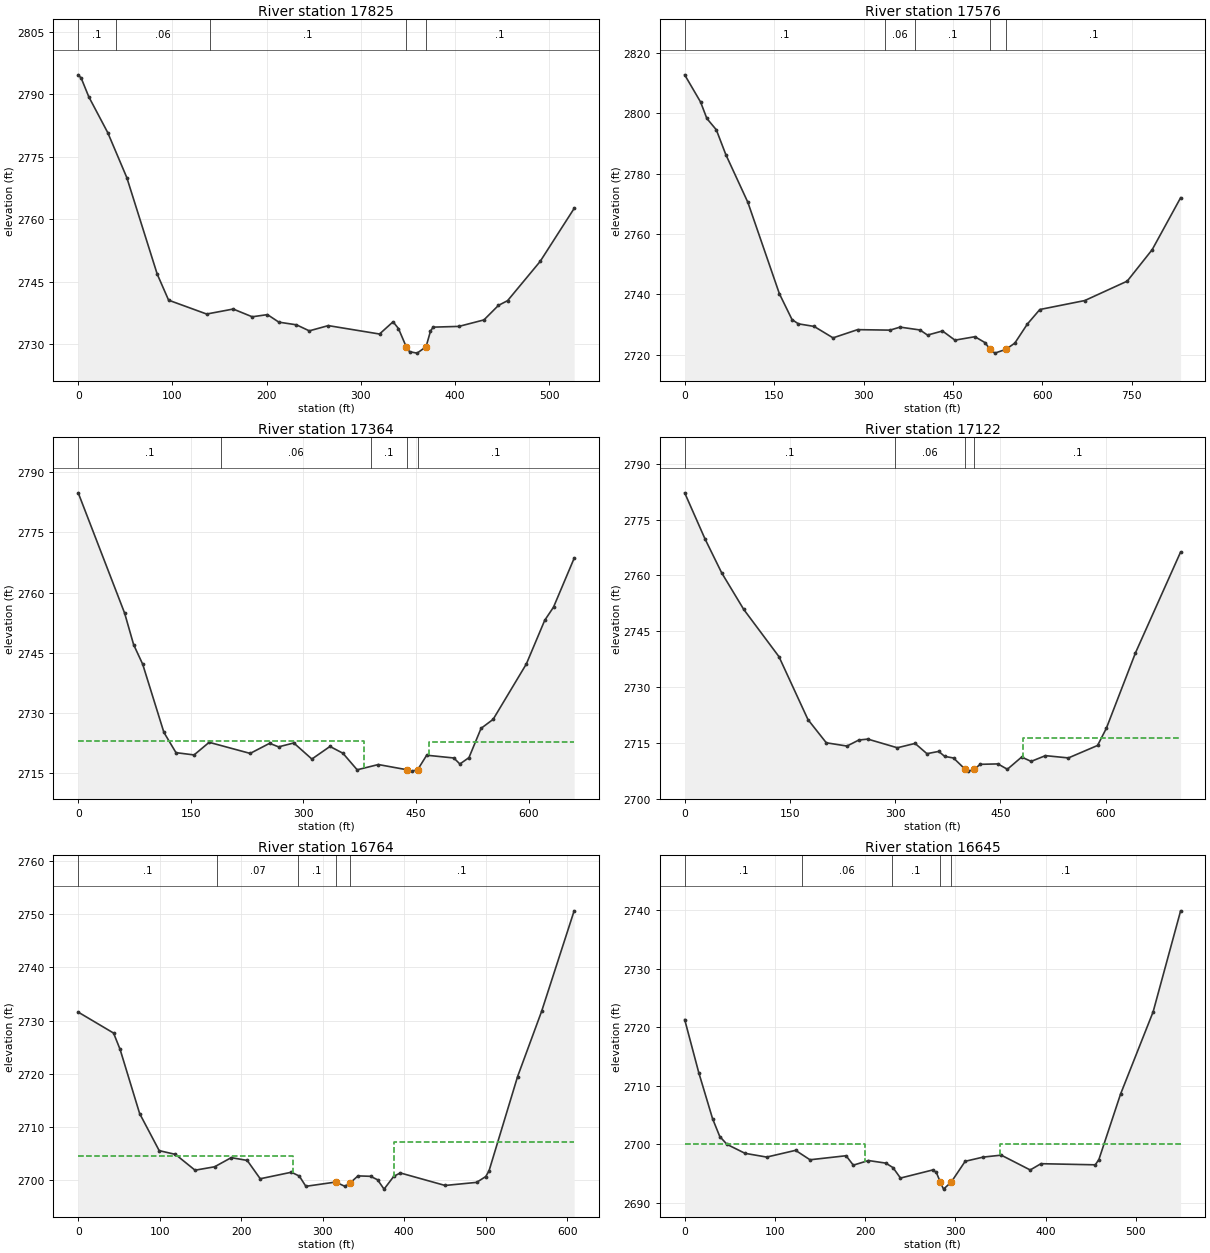
Type RM Length L Ch R = 1 ,17825   ,248.6,248.6,248.6
XS GIS Cut Line= 4
2172819.32109472421738.906046426 2172529.2721607421699.542262523
2172392.53480609 421815.561836132172359.38635649421859.069176233
#Sta/Elev= 30
       0 2794.65     3.2 2793.85    11.2 2789.39    31.4 2780.75    51.6 2769.97
    83.9 2746.78      96 2740.52   136.4 2737.19   164.6 2738.39   184.8 2736.53
     201 2737.05   213.1 2735.24   231.8  2734.6   245.4 2733.15   265.6 2734.41
     320 2732.39   334.4 2735.33   340.1 2733.71   348.6 2729.21   351.9 2728.14
   359.9  2727.8   369.4 2729.32   374.1 2733.06   376.9 2734.04   404.3 2734.22
   430.9 2735.78   446.3 2739.27     456  2740.4   490.6 2749.83   526.7 2762.56
#Mann= 5 ,-1,0
       0      .1       0      40     .06       0     140      .1       0
   348.6    .045       0   369.4      .1       0
Bank Sta=348.6,369.4
XS Rating Curve= 0 ,0
Exp/Cntr(USF)=0,0
Exp/Cntr=0.3,0.1

Type RM Length L Ch R = 1 ,17576   ,210.7,212.3,214.6
XS GIS Cut Line= 4
2172848.32598812421610.4558042172172647.36351241421436.426443807
2172272.37167628421552.4460174142172106.62942827421604.240469917
#Sta/Elev= 30
       0 2812.71    26.7 2803.69    37.2 2798.25    53.1 2794.49      69 2786.29
     106 2770.46   158.9 2740.18   180.1 2731.61   190.7 2730.21   217.1 2729.35
   248.9 2725.56   290.1 2728.28   344.5 2728.12   361.3 2729.12   394.8 2728.17
   407.4 2726.48   432.5 2727.84   453.4  2724.8   486.9 2725.94   503.7    2724
     512 2721.87   520.4  2720.5   539.1 2721.77   553.9 2723.83   574.8 2730.11
   595.8 2734.95   671.2 2737.92   742.4 2744.35   784.3 2754.78     832 2771.99
#Mann= 5 ,-1,0
       0      .1       0  335.84     .06       0  385.84      .1       0
     512    .045       0   539.1      .1       0
Bank Sta=512,539.1
XS Rating Curve= 0 ,0
Exp/Cntr(USF)=0,0
Exp/Cntr=0.3,0.1

Type RM Length L Ch R = 1 ,17364   ,237.2,242,247.7
XS GIS Cut Line= 2
2172769.59842031421266.5406395962172112.84476257   421336.981095
#Sta/Elev= 30
       0 2784.85    61.8 2754.91    73.8 2747.06    85.9 2742.18   114.1 2725.23
   130.2 2720.18   154.3 2719.61   174.4 2722.75     229 2719.99   254.9  2722.5
   266.9 2721.62   287.1 2722.59   311.2 2718.59   335.3 2721.72   352.5 2720.04
   371.5 2715.91   399.7 2717.22   437.3 2715.94     444 2715.58     452 2715.91
   464.1 2719.54   500.3 2718.85   508.3 2717.35   520.4 2718.94   536.5 2726.22
   552.6 2728.47   596.8 2742.24   621.3 2753.12     633 2756.39   660.5 2768.57
#Mann= 5 ,-1,0
       0      .1       0     190     .06       0     390      .1       0
   437.3    .045       0     452      .1       0
#XS Ineff= 2 , 0
          380.17  2723.1  466.54         2722.84
Permanent Ineff=
       F       F
Bank Sta=437.3,452
XS Rating Curve= 0 ,0
Exp/Cntr(USF)=0,0
Exp/Cntr=0.3,0.1

Type RM Length L Ch R = 1 ,17122   ,361.3,358.1,354.3
XS GIS Cut Line= 3
2172767.52664221421208.5308527922172299.30479159421051.075717182
2172094.19875967421109.085503986
#Sta/Elev= 30
       0 2782.17    28.9 2769.82    52.7 2760.68    84.2 2750.83   134.4 2738.14
   175.8 2721.21   201.9 2714.98   231.4  2714.1   248.3 2715.72   261.1 2715.97
   303.2 2713.64   328.5 2714.81   345.4 2712.05   362.2 2712.66   370.7 2711.32
   383.3 2710.89   399.5 2707.93   404.4 2707.36   412.9 2707.84   421.3 2709.19
   446.6  2709.3   460.1 2707.86   480.4 2711.14     494 2709.98   514.4 2711.52
   547.1 2710.91   588.7 2714.26   601.2 2718.87   642.7 2739.14   707.1 2766.27
#Mann= 4 ,-1,0
       0      .1       0     300     .06       0   399.5    .045       0
   412.9      .1       0
#XS Ineff= 2 , 0
                          482.95         2716.21
Permanent Ineff=
       F       F
Bank Sta=399.5,412.9
XS Rating Curve= 0 ,0
Exp/Cntr(USF)=0,0
Exp/Cntr=0.3,0.1

Type RM Length L Ch R = 1 ,16764   ,118.5,118.6,118.7
XS GIS Cut Line= 3
2172655.55052518420746.3089801662172259.25012888420753.213568016
 2172048.4010154420778.701574151
#Sta/Elev= 30
       0 2731.59    43.4 2727.65    51.4 2724.58    75.4 2712.51    99.4 2705.54
   119.4 2704.83   143.4 2701.86   167.4  2702.5   187.8 2704.22   207.4  2703.7
   223.4 2700.25   261.7 2701.48   271.4 2700.75   279.4 2698.83315.9634 2699.63
   327.4 2698.82333.96142699.493   343.4 2700.79   358.8 2700.71   367.4 2700.06
   375.4  2698.3   387.4 2700.72   395.4 2701.34   450.3 2698.99     489 2699.57
   500.2 2700.67   504.2 2701.73   539.3 2719.48   568.7 2731.71   608.7 2750.64
#Mann= 5 ,-1,0
       0      .1       0     170     .07       0     270      .1       0
315.9634    .045       0333.9614      .1       0
#XS Ineff= 2 ,-1
       0  263.83  2704.6   387.1   608.2 2707.24
Permanent Ineff=
       F       F
Bank Sta=315.9634,333.9614
XS Rating Curve= 0 ,0
Exp/Cntr(USF)=0,0
Exp/Cntr=0.3,0.1

Type RM Length L Ch R = 1 ,16645   ,133.3,130.5,127.8
XS GIS Cut Line= 3
2172619.07310649420629.6922473442172273.05996597420634.295526376
2172069.74847543420645.803723954
#Sta/Elev= 30
       0  2721.3    15.6 2712.25    30.9 2704.39    38.9 2701.34    46.9    2700
    66.9 2698.47    90.9 2697.83   122.9 2698.98   138.9 2697.37   178.9 2698.06
   186.9 2696.45   203.7 2697.24   222.9  2696.8   230.9 2696.03   239.2 2694.25
   274.9 2695.63   278.9 2695.22   283.2 2693.62   286.9 2692.36   295.4 2693.55
   310.9 2697.11   330.9 2697.83   350.9 2698.16     383 2695.63   394.9  2696.7
   455.1 2696.51   459.1 2697.41   483.1 2708.57   519.2 2722.61   549.7 2739.86
#Mann= 5 ,-1,0
       0      .1       0     130     .06       0     230      .1       0
   283.2    .045       0   295.4      .1       0
#XS Ineff= 2 , 0
             200    2700     350            2700
Permanent Ineff=
       F       F
Bank Sta=283.2,295.4
XS Rating Curve= 0 ,0
Exp/Cntr(USF)=0,0
Exp/Cntr=0.3,0.1

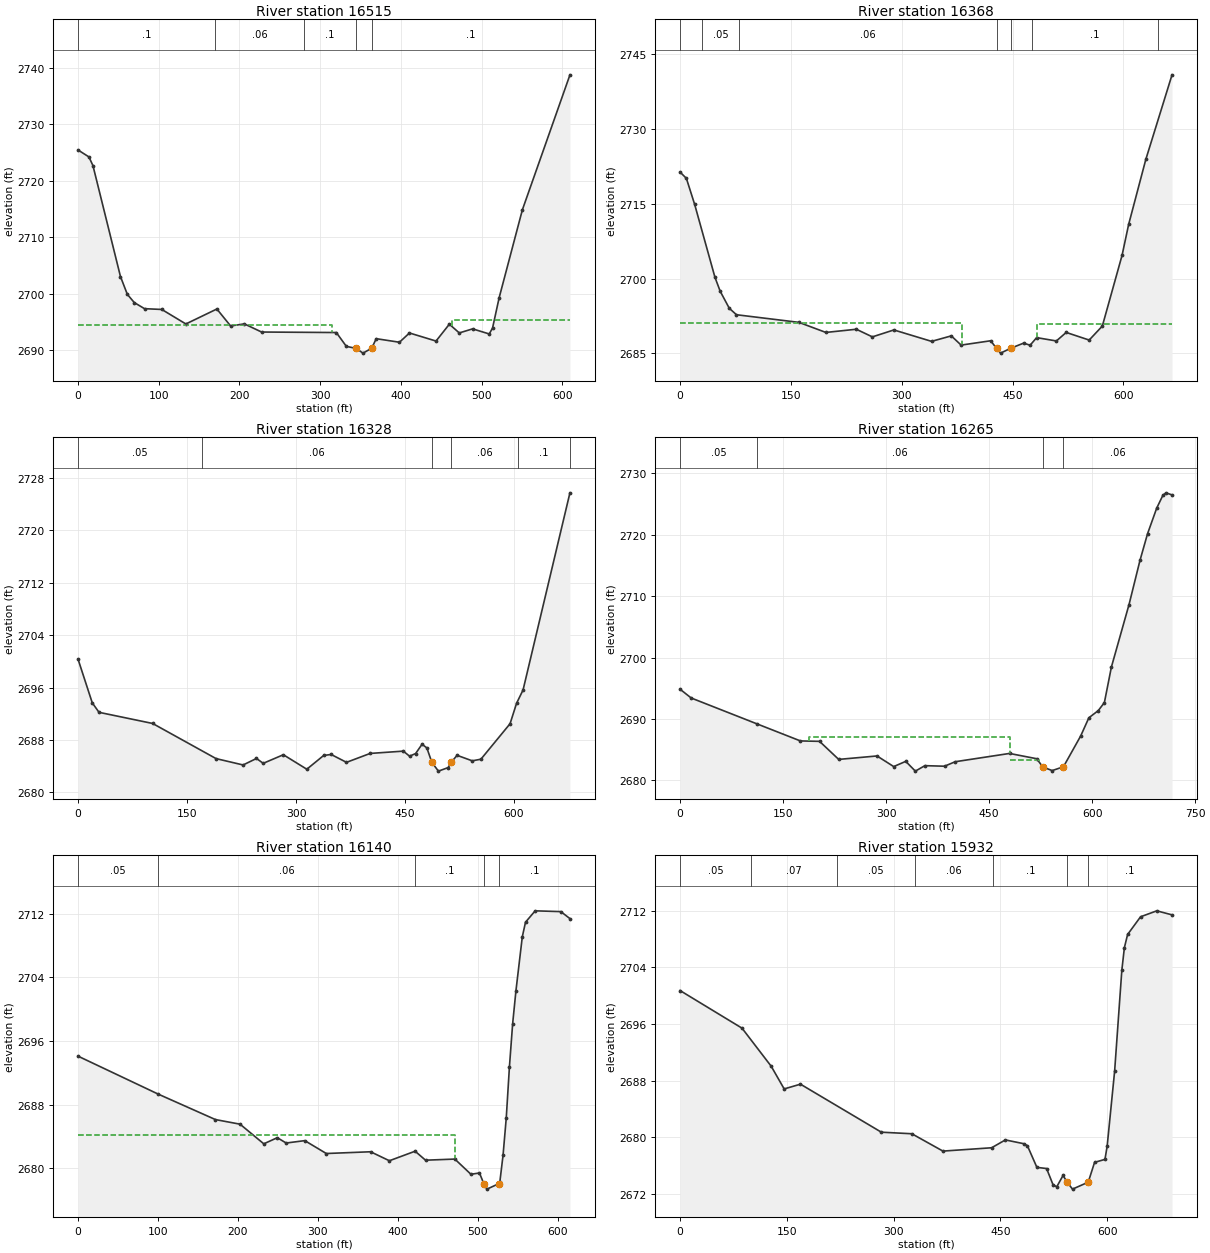
Type RM Length L Ch R = 1 ,16515   ,148.2,146.8,143.1
XS GIS Cut Line= 3
2172645.53574693420589.1739614232172373.98037283420489.192210051
2172062.92603523420564.487109232
#Sta/Elev= 30
       0 2725.45    13.5 2724.22    18.5 2722.68    52.6 2703.01    61.1 2699.86
    69.7  2698.4    82.4 2697.32   103.8 2697.18   133.6 2694.61     172 2697.26
     189 2694.26   206.1 2694.62   227.4 2693.18     320 2693.09   332.4 2690.64
   344.7 2690.27     353 2689.44   363.8  2690.3   369.4    2692   398.2 2691.37
   410.6 2693.01   443.5 2691.58     460 2694.57   472.3 2693.02   488.8 2693.74
   509.4 2692.84   513.5 2693.88   521.7 2699.27   550.5 2714.86   609.4 2738.77
#Mann= 5 ,-1,0
       0      .1       0     170     .06       0     280      .1       0
   344.7    .045       0   363.8      .1       0
#XS Ineff= 2 , 0
          314.46 2694.34  462.72         2695.38
Permanent Ineff=
       F       F
Bank Sta=344.7,363.8
XS Rating Curve= 0 ,0
Exp/Cntr(USF)=0,0
Exp/Cntr=0.3,0.1

Type RM Length L Ch R = 1 ,16368   ,40.3,39.9,40.7
BEGIN DESCRIPTION:
structure xs 4
END DESCRIPTION:
XS GIS Cut Line= 3
2172647.22076891 420497.528704022172385.97024803420319.508749843
2172071.27889079420471.752095517
#Sta/Elev= 30
       0 2721.36     8.5 2720.11    19.7 2714.89    47.2 2700.25    54.3 2697.45
    66.6 2694.04    76.3 2692.75   160.8 2691.22   197.3  2689.2   238.5 2689.84
   260.2 2688.31   289.3  2689.7   340.3 2687.41     367 2688.51   380.3 2686.66
   420.3 2687.53428.3126 2685.98   433.7 2685.05447.51262686.031   464.8 2687.05
   473.7 2686.64   482.5 2688.16   509.2 2687.49   522.5  2689.2   553.6 2687.67
   571.4 2690.48   598.1 2704.67     607 2710.87   630.2 2723.89   665.7 2740.87
#Mann= 7 ,-1,0
       0      .1       0      30     .05       0      80     .06       0
428.3126    .045       0447.5126     .06       0  476.14      .1       0
  646.14     .06       0
#XS Ineff= 2 , 0
          380.86 2691.04   482.7         2690.93
Permanent Ineff=
       F       F
Bank Sta=428.3126,447.5126
XS Rating Curve= 0 ,0
Exp/Cntr(USF)=0,0
Exp/Cntr=0.5,0.3

Type RM Length L Ch R = 1 ,16328   ,62.7,62.8,62.4
BEGIN DESCRIPTION:
structure xs 3; 28.9 ft between structure and xs
END DESCRIPTION:
XS GIS Cut Line= 5
2172653.16457642420371.6021812262172377.24904914420212.915199923
2172337.71442845420270.2414485662172292.07749468420320.355938921
2172094.62017797420420.343578015
#Sta/Elev= 30
       0 2700.34    19.6 2693.67    28.9 2692.22   102.7 2690.52     190 2685.16
   227.2 2684.19   245.6 2685.18   254.9 2684.44   282.6 2685.75   314.9 2683.54
   338.1 2685.64   348.4 2685.79   369.5 2684.59   402.1 2685.95   447.7  2686.3
   456.3 2685.53   464.6 2685.93   473.5 2687.35   480.1 2686.79     487 2684.58
     496 2683.25   509.4 2683.79   513.9 2684.64   521.7 2685.66   542.6 2684.82
   554.5 2685.07   594.6 2690.48   603.6 2693.61   612.5 2695.63     677  2725.7
#Mann= 6 ,-1,0
       0     .05       0     170     .06       0     487    .045       0
   513.9     .06       0  605.71      .1       0  677.04     .06       0
#XS Ineff= 2 ,-1
       0     468  2682.2     543  585.28  2683.3
Permanent Ineff=
       F       F
Bank Sta=487,513.9
XS Rating Curve= 0 ,0
Exp/Cntr(USF)=0,0
Exp/Cntr=0.5,0.3

Type RM Length L Ch R = 1 ,16265   ,120.8,124.7,133.1
BEGIN DESCRIPTION:
structure xs 2; 17 ft between structure and xs
END DESCRIPTION:
XS GIS Cut Line= 4
2172654.85144214 420344.76204111 2172340.2597464420158.275043708
2172265.74435793420264.0601356332172068.28704122420364.047774727
#Sta/Elev= 30
       0 2694.84    16.2 2693.41   112.6 2689.17   175.2 2686.42   203.1 2686.35
     231 2683.41   286.8 2683.97   311.1 2682.24   328.6 2683.09   342.6  2681.5
   356.5 2682.39   385.1  2682.3   400.6 2683.03   479.8 2684.38   519.3 2683.52
   528.3 2682.17   541.9 2681.59558.2756 2682.21   583.4 2687.23   595.3 2690.19
     609 2691.36   617.9 2692.67   628.1 2698.45   653.8 2708.64   669.7 2715.81
   680.7 2720.15   694.1 2724.34   703.1 2726.43   707.6 2726.83   716.4 2726.49
#Mann= 4 ,-1,0
       0     .05       0   112.6     .06       0   528.3    .045       0
558.2756     .06       0
#XS Ineff= 4 ,-1
       0  188.04  2683.3  188.04   480.4    2687   480.4     523  2683.3
   563.5     600  2682.2
Permanent Ineff=
       F       F       F       F
Bank Sta=528.3,558.2756
XS Rating Curve= 0 ,0
Exp/Cntr(USF)=0,0
Exp/Cntr=0.5,0.3

Type RM Length L Ch R = 1 ,16140   ,202.2,208.4,219
BEGIN DESCRIPTION:
structure xs 1
END DESCRIPTION:
XS GIS Cut Line= 4
2172651.77376109420335.4507686662172325.11583196420140.579343406
2172249.16971501420158.1039564992172091.31841703420174.024987763
#Sta/Elev= 30
       0  2694.1   100.6 2689.31   171.9 2686.12   202.7 2685.54   232.4 2683.07
   249.3 2683.84   260.4 2683.17   283.7 2683.47   310.6 2681.85     366 2682.07
   389.5 2680.94   421.7 2682.14   434.7 2681.01   471.4 2681.15   491.5 2679.24
   502.2  2679.4   507.6 2678.07   511.6 2677.37  526.49 2678.06   527.7 2678.28
   531.7 2681.63   535.7  2686.3   539.7 2692.78   543.7 2698.17   547.8  2702.3
   555.8 2709.12   559.8 2710.95   571.9 2712.38     604 2712.28   615.4  2711.4
#Mann= 5 ,-1,0
       0     .05       0   100.6     .06       0   421.7      .1       0
   507.6    .045       0  526.49      .1       0
#XS Ineff= 2 , 0
           471.4  2684.2
Permanent Ineff=
       F       F
Bank Sta=507.6,526.49
XS Rating Curve= 0 ,0
Exp/Cntr(USF)=0,0
Exp/Cntr=0.3,0.1

Type RM Length L Ch R = 1 ,15932   ,217,215,213.3
XS GIS Cut Line= 2
2172772.67303571420246.0267159732172165.37647182419916.457239228
#Sta/Elev= 30
       0 2700.73      87 2695.42     128 2690.04   146.2 2686.84   169.1 2687.51
   282.7 2680.73   325.5 2680.51   369.2 2678.06   437.6 2678.53   456.9 2679.64
     483  2679.1   487.8 2678.83   501.2 2675.76   514.8  2675.6   523.9  2673.3
   529.1 2673.02   537.9 2674.62   543.8 2673.66   551.2 2672.69   573.3 2673.67
   582.2 2676.47   596.8 2676.89   599.9 2678.77   610.4 2689.38   620.5 2703.61
   624.1  2706.8   628.6 2708.65   646.8 2711.15   669.6 2711.99     691 2711.42
#Mann= 7 ,-1,0
       0     .05       0     100     .07       0     220     .05       0
     330     .06       0     440      .1       0   543.8    .045       0
   573.3      .1       0
Bank Sta=543.8,573.3
XS Rating Curve= 0 ,0
Exp/Cntr(USF)=0,0
Exp/Cntr=0.3,0.1

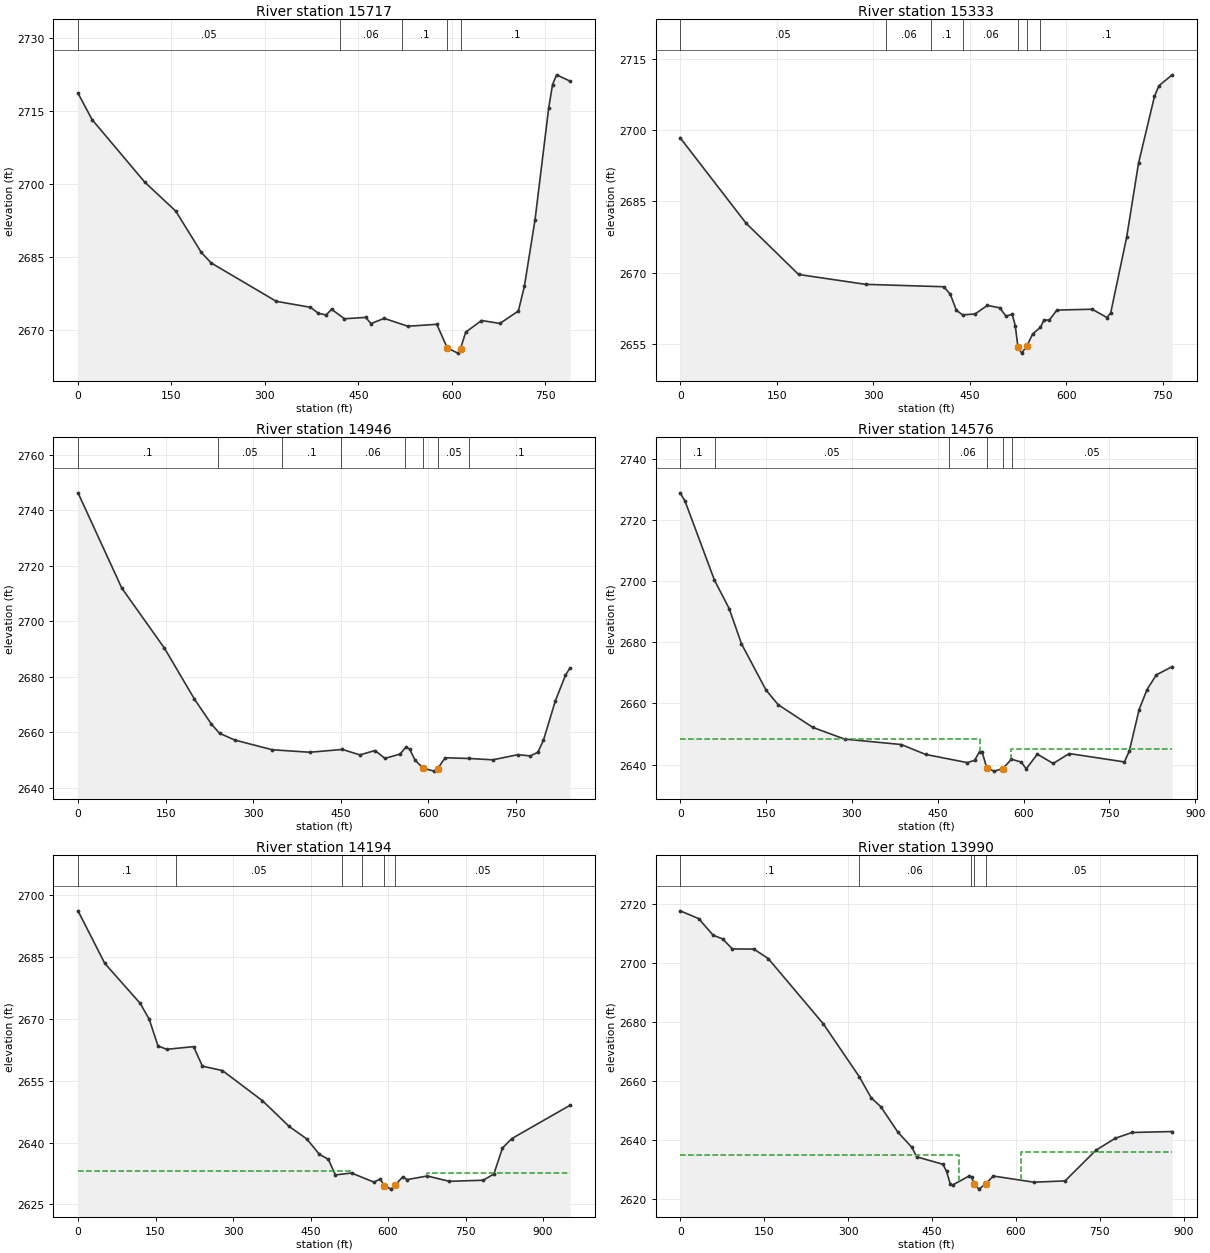
Type RM Length L Ch R = 1 ,15717   ,378.7,384.2,386.9
XS GIS Cut Line= 2
2172977.48651651420003.1966474212172229.57462236419748.367941104
#Sta/Elev= 30
       0 2718.69    22.5 2713.29     107 2700.46   157.1 2694.46     198    2686
   213.8 2683.84   318.3 2675.96   373.3 2674.73   385.9  2673.5   398.6 2673.16
   407.1 2674.33   427.9 2672.38     462 2672.66   470.5 2671.38   491.6 2672.46
   529.6 2670.84   576.1 2671.24     593 2666.37   609.9 2665.32   614.2 2666.26
   622.6 2669.63   647.9 2672.02   677.5 2671.42   707.1 2673.97   716.8 2679.06
   733.9 2692.74   755.9 2715.76     762 2720.46   768.5 2722.47   790.1 2721.18
#Mann= 5 ,-1,0
       0     .05       0     420     .06       0     520      .1       0
     593    .045       0   614.2      .1       0
Bank Sta=593,614.2
XS Rating Curve= 0 ,0
Exp/Cntr(USF)=0,0
Exp/Cntr=0.3,0.1

Type RM Length L Ch R = 1 ,15333   ,389.2,387.3,384.9
XS GIS Cut Line= 2
2173049.28846383419812.1524133042172413.25258709419387.437902777
#Sta/Elev= 30
       0  2698.4   102.3 2680.42   184.1  2669.6   288.5 2667.52   409.6 2667.02
   419.8 2665.45   429.4 2662.04     439 2661.09   458.3 2661.28   477.5 2663.09
   496.7 2662.58   506.4 2660.83     516 2661.21   520.8 2658.85     525 2654.32
   530.7 2653.03   538.4 2654.44     548  2657.1     560 2658.45   565.3 2659.97
     574 2660.03   585.5  2662.1   640.3 2662.28   663.4 2660.53   669.2 2661.52
     694 2677.47   712.4 2693.03   737.2 2707.12   744.1 2709.37   764.8 2711.67
#Mann= 7 ,-1,0
       0     .05       0     320     .06       0     390      .1       0
     440     .06       0     525    .045       0   538.4     .06       0
     560      .1       0
Bank Sta=525,538.4
XS Rating Curve= 0 ,0
Exp/Cntr(USF)=0,0
Exp/Cntr=0.3,0.1

Type RM Length L Ch R = 1 ,14946   ,369.5,370,369
XS GIS Cut Line= 2
2173302.04539205419379.150790377 2172516.8414921419072.527631557
#Sta/Elev= 30
       0 2746.28      75 2711.91   148.1 2690.25   199.5 2671.87   228.4  2662.9
   242.5 2659.56   268.2 2657.15   332.7 2653.62   397.1 2652.72   452.9 2653.73
     483 2651.76   508.7 2653.34   525.9 2650.51   551.7 2652.07   561.9 2654.62
   568.1 2653.85   577.5 2649.84   591.6 2646.93   610.2 2645.91   616.1  2646.8
     629 2650.73     670 2650.47   710.5 2649.99   753.7 2651.85     775 2651.38
   787.8 2652.75   797.2 2656.98   817.9 2671.36   835.1 2680.51   842.9 2683.16
#Mann= 8 ,-1,0
       0      .1       0     240     .05       0     350      .1       0
     450     .06       0     560     .05       0   591.6    .045       0
   616.1     .05       0     670      .1       0
Bank Sta=591.6,616.1
XS Rating Curve= 0 ,0
Exp/Cntr(USF)=0,0
Exp/Cntr=0.3,0.1

Type RM Length L Ch R = 1 ,14576   ,381.3,381.8,382.7
XS GIS Cut Line= 2
2173415.99318755419029.020291455 2172614.2150628418718.253576435
#Sta/Elev= 30
       0  2728.9     8.4 2726.22    59.9 2700.33    85.6 2691.04   107.1 2679.53
     150 2664.37   171.4 2659.57   231.6 2652.19   287.3 2648.34   386.2 2646.57
   428.8 2643.33   501.7 2640.65   514.6 2641.38   523.2 2644.27   527.5 2644.24
     536 2638.78   548.9 2637.86     564  2638.7   578.9 2641.76   596.1 2640.82
   604.7  2638.6   624.2 2643.41   651.9 2640.36   679.9 2643.61   776.3 2640.87
     785 2644.48     802 2657.96   815.9 2664.55   832.1 2669.34   859.9 2672.05
#Mann= 6 ,-1,0
       0      .1       0      60     .05       0     470     .06       0
     536    .045       0     564     .06       0     580     .05       0
#XS Ineff= 2 , 0
          523.38  2648.3  577.46         2645.02
Permanent Ineff=
       F       F
Bank Sta=536,564
XS Rating Curve= 0 ,0
Exp/Cntr(USF)=0,0
Exp/Cntr=0.3,0.1

Type RM Length L Ch R = 1 ,14194   ,203.8,203.8,203.4
XS GIS Cut Line= 2
2173643.88877857418720.3253545352172759.23952981418368.123077513
#Sta/Elev= 30
       0 2696.25    51.8 2683.49   120.2  2673.8   137.7 2669.96   154.7 2663.46
   171.6 2662.63   223.6 2663.27   240.8 2658.53   279.5 2657.47     357 2650.14
   408.6 2643.91   442.6 2640.87   467.2 2637.12   484.3 2635.94     498 2632.13
   529.3 2632.59   572.3  2630.4   585.2 2631.11   592.5 2629.49   605.8 2628.68
   614.1 2629.64   628.3 2631.68   636.9 2630.99   675.6 2631.87   718.7 2630.58
   784.4 2630.84   804.8 2632.37   821.3 2638.63   839.2 2640.93   952.2 2649.04
#Mann= 6 ,-1,0
       0      .1       0     190     .05       0     510     .06       0
     550     .08       0   592.5    .045       0   614.1     .05       0
#XS Ineff= 2 , 0
          525.59 2632.98  674.72          2632.6
Permanent Ineff=
       F       F
Bank Sta=592.5,614.1
XS Rating Curve= 0 ,0
Exp/Cntr(USF)=0,0
Exp/Cntr=0.3,0.1

Type RM Length L Ch R = 1 ,13990   ,377.9,362.8,341.2
XS GIS Cut Line= 2
2173671.27445545418504.369293923 2172849.2022775418192.080613711
#Sta/Elev= 30
       0 2717.62    32.8 2715.01    58.9 2709.38    76.1 2708.09    93.2 2704.72
   131.7 2704.68   157.4 2701.47   255.8 2679.39     320 2661.54   341.3 2654.38
   358.5 2651.37   389.4 2642.66   414.1 2637.63   422.6  2634.4   469.7 2631.87
     476 2629.53   482.6  2625.3   486.8 2624.86   516.8 2627.96   521.1 2627.42
   525.3 2625.19   533.9 2623.47  545.722625.197   559.6  2627.9   632.3 2625.82
   687.9 2626.25   742.9 2636.62   777.8  2640.7   807.7 2642.63   879.4 2642.96
#Mann= 5 ,-1,0
       0      .1       0     320     .06       0     520      .1       0
   525.3    .045       0  545.72     .05       0
#XS Ineff= 2 , 0
           497.7 2635.07  608.29         2636.18
Permanent Ineff=
       F       F
Bank Sta=525.3,545.72
XS Rating Curve= 0 ,0
Exp/Cntr(USF)=0,0
Exp/Cntr=0.3,0.1

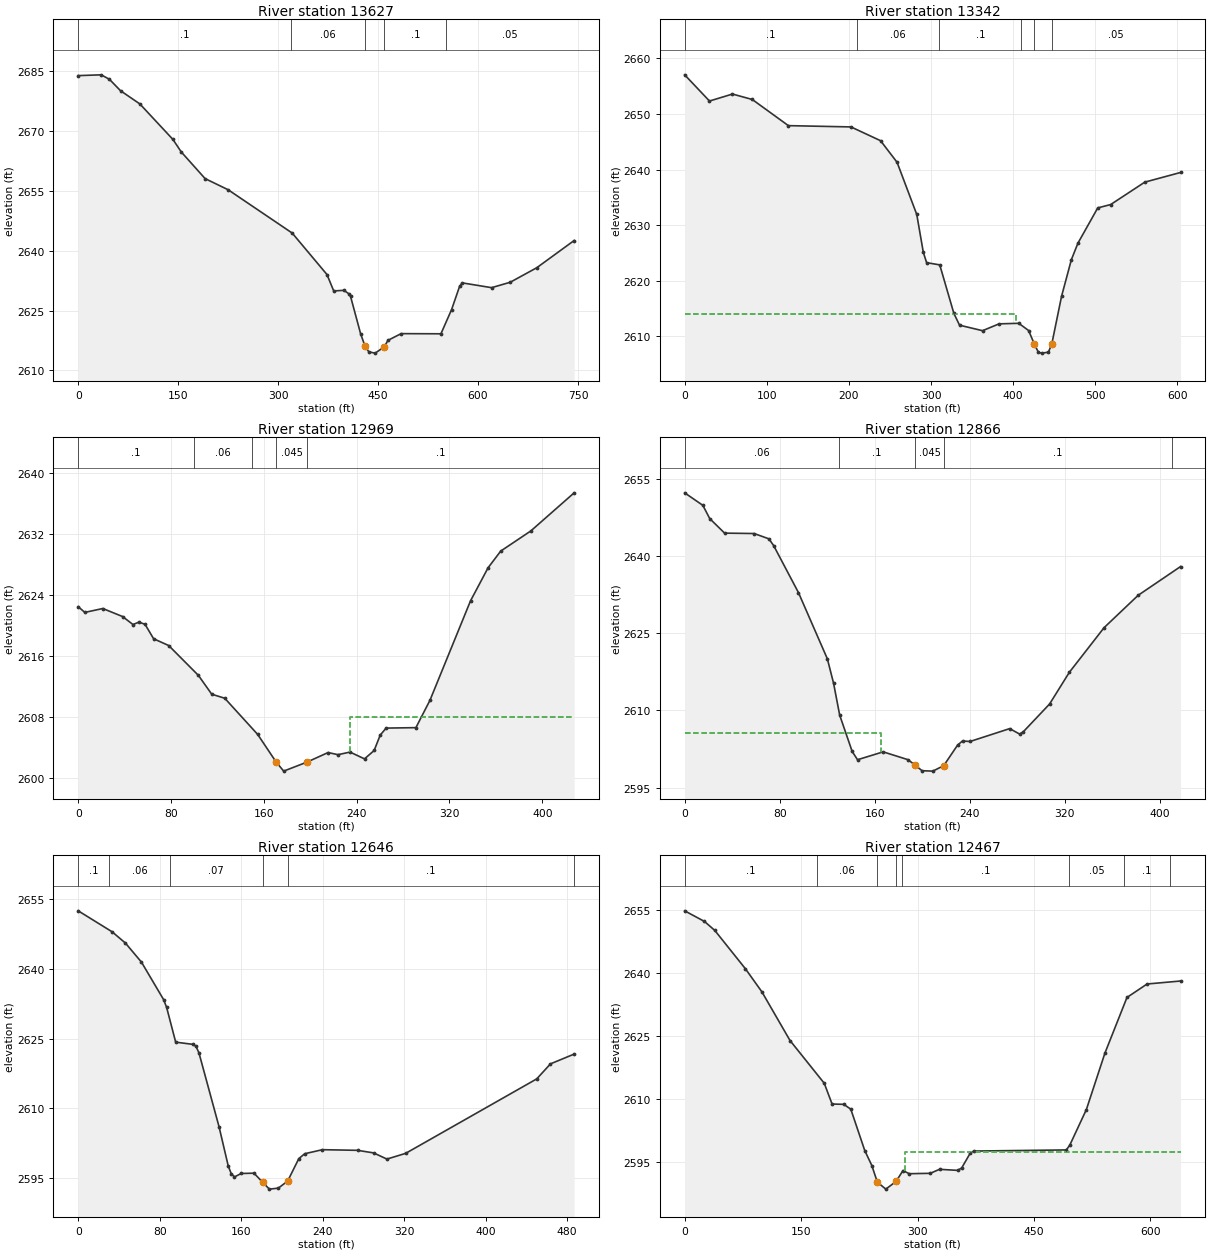
Type RM Length L Ch R = 1 ,13627   ,275.7,285.3,295.8
XS GIS Cut Line= 4
2173581.50473905418020.937321333 2173239.1566271417929.431556473
2173106.34110889418031.9304890032172884.31841968418028.034148739
#Sta/Elev= 30
       0 2683.92    34.5 2684.12    46.9 2682.99    63.5 2680.13    92.5 2676.82
   142.2  2667.9   154.6 2664.78   190.4 2658.09     225 2655.29   321.1 2644.43
   373.3 2634.02   383.4 2629.91   398.6 2630.06   406.3 2629.19   408.7 2628.52
   423.8 2619.15   430.5 2616.01   436.2 2614.62   445.6 2614.31  459.422615.895
   464.7 2617.51   484.6  2619.2   544.3 2619.16   560.3 2625.24   572.3 2631.06
   576.3 2631.93   620.3 2630.73   648.3 2632.09   688.2 2635.74   744.2 2642.56
#Mann= 5 ,-1,0
       0      .1       0     320     .06       0   430.5    .045       0
  459.42      .1       0  552.13     .05       0
Bank Sta=430.5,459.42
XS Rating Curve= 0 ,0
Exp/Cntr(USF)=0,0
Exp/Cntr=0.3,0.1

Type RM Length L Ch R = 1 ,13342   ,385.9,372.6,363.3
XS GIS Cut Line= 2
2173482.29008676417707.2258635712172879.40265962417742.446091274
#Sta/Elev= 30
       0 2657.06    30.2 2652.34    58.2  2653.6    82.3 2652.62   126.3 2647.91
   202.5 2647.68   238.5  2645.2   258.6 2641.32   282.6 2631.92   290.6 2625.09
   294.6 2623.24   310.6 2622.84   327.8  2614.1   334.7 2611.98   362.7 2610.99
   382.8 2612.22   406.8 2612.32   418.8 2611.02   425.7 2608.61   430.8 2607.07
   434.9 2606.95   442.9 2607.12     447 2608.57   458.9 2617.17   470.9 2623.79
   478.9 2626.76     503  2633.1   518.7  2633.7   560.3 2637.74   603.9 2639.48
#Mann= 6 ,-1,0
       0      .1       0     210     .06       0     310      .1       0
     410     .05       0   425.7    .045       0     447     .05       0
#XS Ineff= 2 , 0
          403.04 2614.02
Permanent Ineff=
       F       F
Bank Sta=425.7,447
XS Rating Curve= 0 ,0
Exp/Cntr(USF)=0,0
Exp/Cntr=0.3,0.1

Type RM Length L Ch R = 1 ,12969   ,105.7,103.5,104.7
XS GIS Cut Line= 2
2173152.53781088417243.6992613762172823.38630923417516.548532478
#Sta/Elev= 30
       0 2622.47     5.7 2621.72    21.2 2622.23    38.2 2621.18    47.2 2620.13
    52.3 2620.44    57.6 2620.16      65 2618.26      78 2617.37   103.6 2613.45
   115.1 2610.98   126.3 2610.45   154.7  2605.7  170.422602.117   177.1 2600.88
   197.3 2602.07   215.4 2603.32   223.9 2603.04   234.3 2603.38   246.8 2602.49
   255.1 2603.59   260.3  2605.6   265.4 2606.53   291.1 2606.59   303.2 2610.18
   338.2 2623.25   353.3 2627.58   364.2 2629.77   390.1 2632.41   427.5 2637.42
#Mann= 5 ,-1,0
       0      .1       0     100     .06       0     150      .1       0
  170.42    .045       0   197.3      .1       0
#XS Ineff= 2 , 0
                          234.37         2608.03
Permanent Ineff=
       F       F
Bank Sta=170.42,197.3
XS Rating Curve= 0 ,0
Exp/Cntr(USF)=0,0
Exp/Cntr=0.3,0.1

Type RM Length L Ch R = 1 ,12866   ,218.3,220,221.7
XS GIS Cut Line= 2
2173080.11177339417175.5733128512172760.50633952417444.120592235
#Sta/Elev= 30
       0 2652.23    15.3  2649.8    21.1 2647.23    33.6 2644.41    58.5 2644.33
    70.9  2643.3    74.9 2641.99    95.8 2632.86   120.1 2620.02   125.3 2615.32
   130.5 2609.08     141 2602.04   145.5 2600.43   167.1 2601.96     188 2600.44
194.20452599.349   199.8  2598.3   208.9 2598.22 218.0822599.286   229.8 2603.29
   233.9 2604.07   240.2 2603.97   273.6 2606.47     282 2605.41     285 2605.84
   307.2 2611.25   323.8 2617.39   353.1 2626.07   381.8 2632.35   417.5 2637.93
#Mann= 5 ,-1,0
       0     .06       0     130      .1       0194.2045    .045       0
 218.082      .1       0     410     .05       0
#XS Ineff= 2 , 0
          165.07 2605.59
Permanent Ineff=
       F       F
Bank Sta=194.2045,218.082
XS Rating Curve= 0 ,0
Exp/Cntr(USF)=0,0
Exp/Cntr=0.3,0.1

Type RM Length L Ch R = 1 ,12646   ,176.7,179.2,181.9
XS GIS Cut Line= 3
2172951.87088663417028.595867757 2172654.4796176417226.375498132
2172595.29009318417341.867253095
#Sta/Elev= 30
       0 2652.45    33.3 2647.94    46.4 2645.51    62.1 2641.42    83.9 2633.34
    86.8 2631.69    95.7 2624.22   112.7 2623.74   115.6 2623.32   118.5 2621.95
   138.3 2606.01   147.3  2597.6   150.2 2595.97   153.4 2595.24     160 2595.98
   172.6 2596.05     1812594.108   187.7 2592.62   196.4 2592.83   205.62594.335
   216.6 2599.18   222.4 2600.23   239.8  2601.1   274.3 2600.96     290 2600.41
   303.1 2599.08   321.5 2600.31   450.2 2616.32   463.7 2619.55   486.9 2621.65
#Mann= 6 ,-1,0
       0      .1       0      30     .06       0      90     .07       0
     181    .045       0   205.6      .1       0  486.93     .05       0
Bank Sta=181,205.6
XS Rating Curve= 0 ,0
Exp/Cntr(USF)=0,0
Exp/Cntr=0.3,0.1

Type RM Length L Ch R = 1 ,12467   ,280.1,283,284.8
XS GIS Cut Line= 3
2172935.34066832416872.299289219  2172639.775935417009.125909688
2172440.74047815417250.905567696
#Sta/Elev= 30
       0 2654.69    25.5 2652.17    38.8 2650.04    78.3 2640.93    99.5 2635.46
   135.7 2623.92   179.8 2613.78   189.9 2608.85   204.9 2608.78     214 2607.63
     232 2597.81   241.1 2594.26248.18292590.333   259.1 2588.66272.38132590.495
   281.2 2593.06   289.3 2592.32   316.4 2592.41   328.3 2593.36   351.7 2593.11
   356.9  2593.7   368.1 2597.27   372.4 2597.69   491.6 2597.96     496 2599.05
   517.5 2607.55   541.4 2620.94   569.8 2634.14   595.7 2637.33   638.9 2638.04
#Mann= 8 ,-1,0
       0      .1       0     170     .06       0248.1829    .045       0
272.3813     .06       0     280      .1       0   495.7     .05       0
   565.7      .1       0   625.7     .05       0
#XS Ineff= 2 , 0
                          283.55         2597.47
Permanent Ineff=
       F       F
Bank Sta=248.1829,272.3813
XS Rating Curve= 0 ,0
Exp/Cntr(USF)=0,0
Exp/Cntr=0.3,0.1