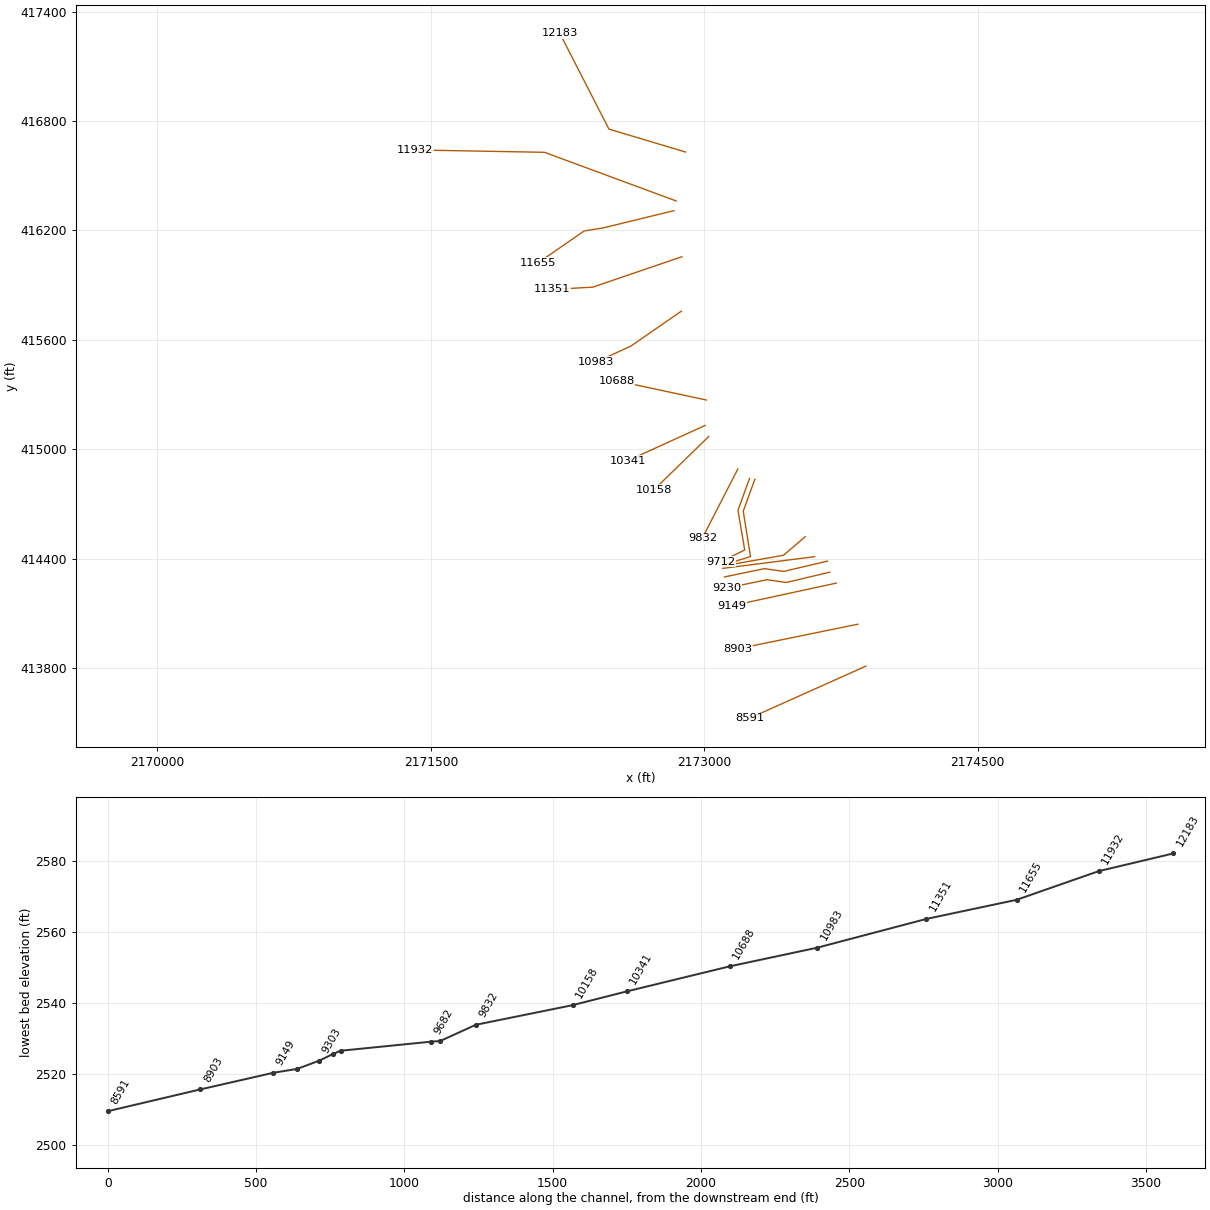
HEC-RAS study BRFFYCK.prj: BRFFYCK

--- BRFFYCK.g01 (geometry) --- (continued)

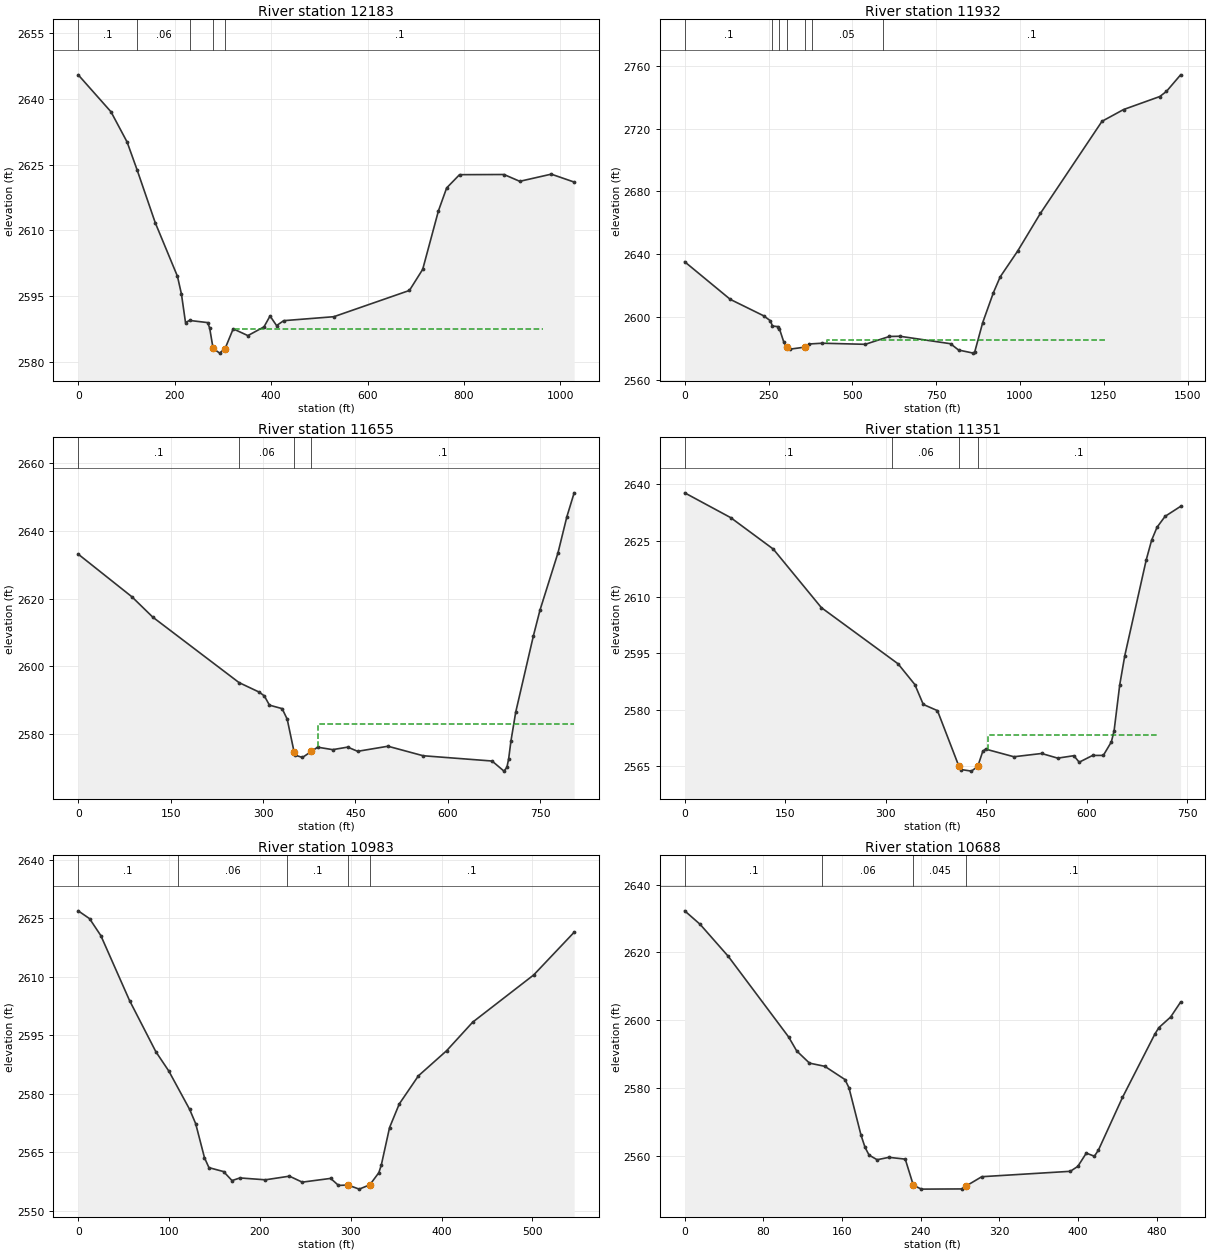
Type RM Length L Ch R = 1 ,12183   ,253.3,252,250.6
XS GIS Cut Line= 3
2172897.30188455416630.1914703372172476.79673015416756.037399161
2172207.81000183 417280.61447574
#Sta/Elev= 30
       0 2645.42      68    2637   101.4 2630.12   122.4  2623.7   159.8 2611.74
   205.8 2599.56   214.1 2595.51   222.5 2589.04   230.8 2589.51   268.4 2589.02
   272.6 2587.78   279.7 2583.15   293.4 2582.07  304.65 2583.12   321.4  2587.6
   351.9 2586.06   385.3 2588.05   397.8 2590.52   411.4 2588.34   426.2 2589.46
   530.1 2590.36   686.9 2596.34   714.4 2601.14   747.1 2614.48   764.1 2619.68
   790.8 2622.69     883 2622.73   915.7 2621.18   981.1 2622.81  1028.5 2621.01
#Mann= 5 ,-1,0
       0      .1       0   122.4     .06       0   230.8      .1       0
   279.7    .045       0  304.65      .1       0
#XS Ineff= 1 ,-1
     325   964.4 2587.64
Permanent Ineff=
       F
Bank Sta=279.7,304.65
XS Rating Curve= 0 ,0
Exp/Cntr(USF)=0,0
Exp/Cntr=0.3,0.1

Type RM Length L Ch R = 1 ,11932   ,265.7,276.9,288.6
XS GIS Cut Line= 3
2172845.28101781416362.0396572062172123.46564431416628.686748124
2171414.09611067416641.734400795
#Sta/Elev= 30
       0 2635.25     136  2611.3   235.7 2600.83   255.5 2597.68   261.8 2594.31
   278.4 2593.94   282.6 2592.56   295.4 2584.24   303.9 2581.09   314.4 2579.61
   359.4 2580.92   372.2 2582.91   410.5 2583.38   538.5 2582.68   610.5 2587.69
   641.7 2587.81   792.8 2583.06   816.8 2579.04   860.8 2577.07   864.8 2577.68
   888.8 2596.53   920.8 2615.64   940.8 2625.59   992.8 2641.99  1060.8 2666.06
  1244.6  2724.7  1308.9 2732.18  1416.9 2740.46  1436.7 2743.72    1479 2754.28
#Mann= 7 ,-1,0
       0      .1       0     260     .06       0     280      .1       0
   303.9    .045       0   359.4      .1       0     380     .05       0
     590      .1       0
#XS Ineff= 1 ,-1
   423.9  1257.6 2585.31
Permanent Ineff=
       F
Bank Sta=303.9,359.4
XS Rating Curve= 0 ,0
Exp/Cntr(USF)=0,0
Exp/Cntr=0.3,0.1

Type RM Length L Ch R = 1 ,11655   ,301.6,303.9,304.8
XS GIS Cut Line= 4
2172833.82354142416308.7756459832172446.46712088416214.293624642
2172341.07093068416197.2836279212172088.97767706416023.043725392
#Sta/Elev= 30
       0 2633.15    87.1 2620.55   121.1 2614.52   261.1 2595.17     294 2592.34
   302.2 2591.22   310.5  2588.5   331.1 2587.47   339.3 2584.36350.39942574.758
   351.9 2573.74     364 2573.03   378.5  2574.8   388.7 2576.07   413.2 2575.34
   437.5 2576.09   453.7 2574.85   502.9 2576.35     560 2573.54   671.9 2571.98
   691.3 2568.99     696 2570.11   698.8 2572.54   702.6 2577.92   710.3 2586.42
   739.1 2609.05   749.7 2616.58   778.9  2633.5   793.4 2644.23   805.2 2651.28
#Mann= 4 ,-1,0
       0      .1       0   261.1     .06       0350.3994    .045       0
   378.5      .1       0
#XS Ineff= 2 , 0
                          389.86         2582.79
Permanent Ineff=
       F       F
Bank Sta=350.3994,378.5
XS Rating Curve= 0 ,0
Exp/Cntr(USF)=0,0
Exp/Cntr=0.3,0.1

Type RM Length L Ch R = 1 ,11351   ,362.9,367.6,372.6
XS GIS Cut Line= 3
2172877.33088152416056.0187177672172387.86583366 415889.01683491
2172164.99739188415876.567442274
#Sta/Elev= 30
       0 2637.75    68.8 2631.13   132.3 2622.76   204.1 2607.16   318.5 2592.21
   343.6 2586.68   356.2 2581.38   377.4 2579.72 409.199 2564.99   412.8 2564.03
   428.1 2563.61437.49892564.853     445 2568.87   449.2 2569.48   491.5 2567.44
   532.9 2568.31   556.9 2567.07     581 2567.72     589 2565.99     609 2567.79
     625  2567.8     637  2571.4   641.1 2574.38   649.5  2586.6     657 2594.33
   689.1 2619.91   697.1 2625.12   705.2 2628.58   717.2 2631.48   740.4 2634.15
#Mann= 4 ,-1,0
       0      .1       0     310     .06       0 409.199    .045       0
437.4989      .1       0
#XS Ineff= 1 ,-1
  453.41   707.6 2573.36
Permanent Ineff=
       F
Bank Sta=409.199,437.4989
XS Rating Curve= 0 ,0
Exp/Cntr(USF)=0,0
Exp/Cntr=0.3,0.1

Type RM Length L Ch R = 1 ,10983   ,324.4,295.3,274.9
XS GIS Cut Line= 3
2172874.48583953415757.5395149412172597.73674834415565.944585778
2172407.50340286415478.572725698
#Sta/Elev= 30
       0 2626.85    12.5 2624.84    24.9  2620.5    56.5 2603.86    85.5 2590.72
    99.7 2585.79   122.7 2575.93   129.3 2572.29     139 2563.55   143.9 2561.02
     160 2560.01   169.3  2557.7     178 2558.38     206  2557.9   232.5 2558.83
   246.6  2557.3   277.9 2558.26   286.5 2556.46296.88412556.561   309.3 2555.51
     321 2556.62   330.9 2559.72   333.6 2561.66   342.7 2571.28   353.4 2577.35
   374.5 2584.56   405.5 2590.99   434.3 2598.33   501.4 2610.42   545.9 2621.36
#Mann= 5 ,-1,0
       0      .1       0     110     .06       0     230      .1       0
296.8841    .045       0     321      .1       0
Bank Sta=296.8841,321
XS Rating Curve= 0 ,0
Exp/Cntr(USF)=0,0
Exp/Cntr=0.3,0.1

Type RM Length L Ch R = 1 ,10688   ,333,347.2,358.5
XS GIS Cut Line= 2
 2173011.5360629415269.8940275532172518.45287507415375.554710659
#Sta/Elev= 30
       0 2632.26    15.7 2628.28    44.3 2618.86   105.7 2595.09   113.9 2590.98
   126.9 2587.38   142.5 2586.44     163 2582.54   167.1 2580.09   179.3 2566.16
   183.4 2562.56   187.5 2560.28   195.7 2558.91   207.7 2559.62   224.3 2559.09
   232.5  2551.4   240.7 2550.25   281.6 2550.31   286.5 2551.23   302.1 2553.91
   392.1  2555.5   399.8 2556.96   408.4 2560.87   416.6 2559.94   420.7 2561.74
   445.2 2577.28     478 2595.88   482.1 2597.82   494.1 2600.95   504.3 2605.37
#Mann= 4 ,-1,0
       0      .1       0     140     .06       0   232.5    .045       0
   286.5      .1       0
Bank Sta=232.5,286.5
XS Rating Curve= 0 ,0
Exp/Cntr(USF)=0,0
Exp/Cntr=0.3,0.1

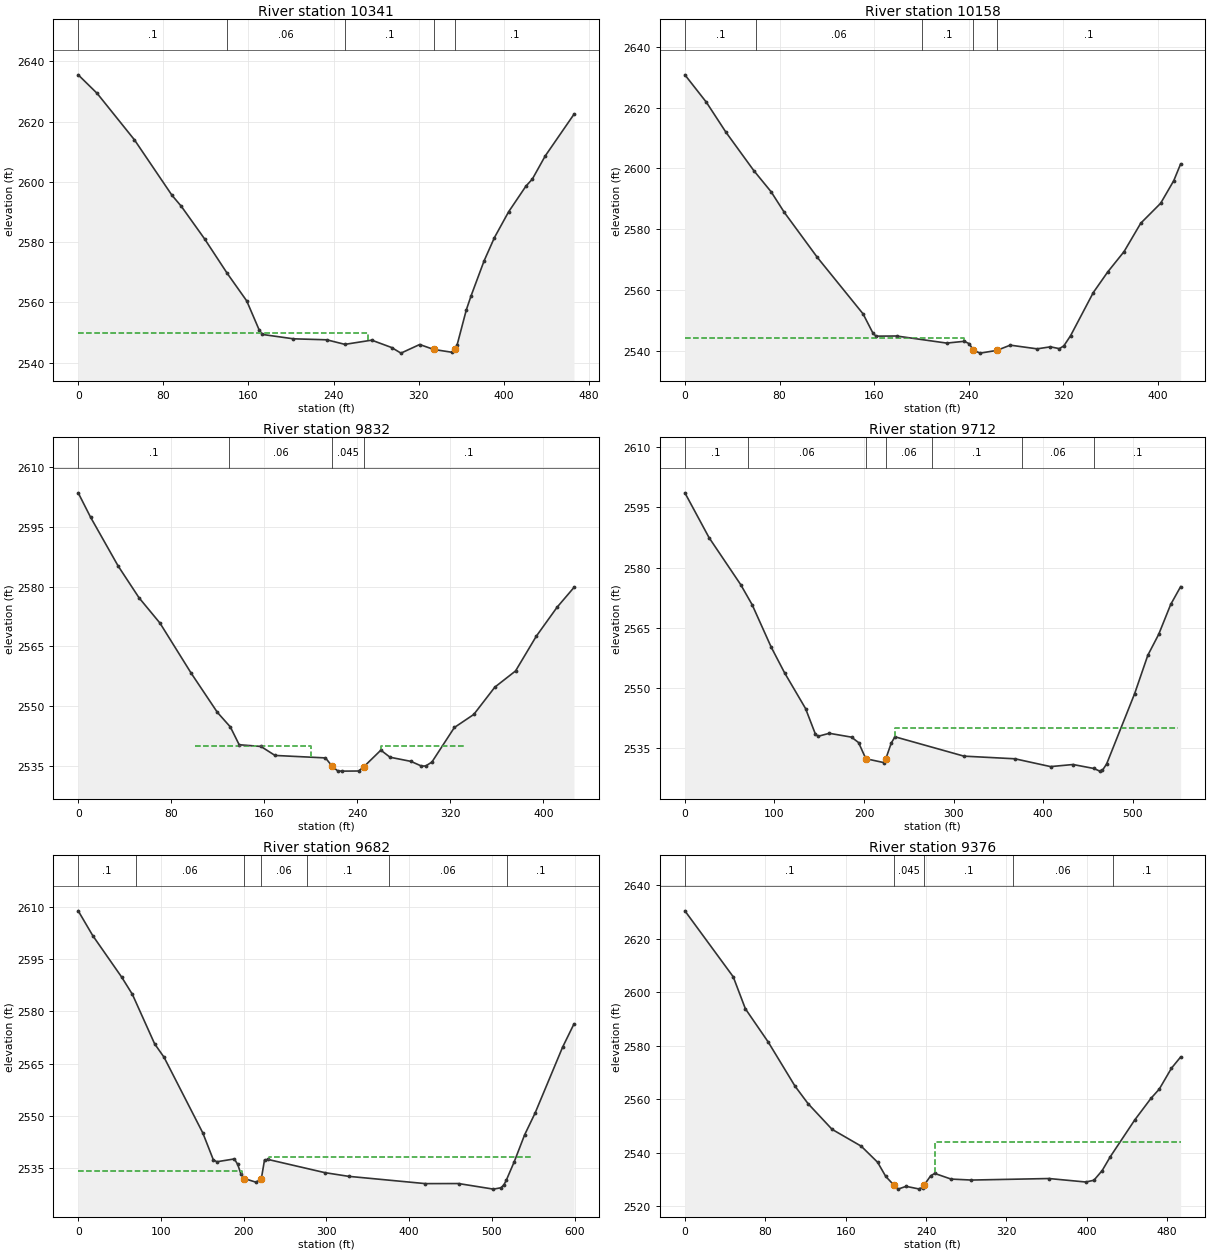
Type RM Length L Ch R = 1 ,10341   ,172.7,182.5,188.9
XS GIS Cut Line= 2
2173004.33346765415130.3770398632172580.21348313414937.348072548
#Sta/Elev= 30
       0  2635.5    17.8 2629.35    52.9 2613.92    88.1 2595.57    96.9  2591.9
   118.8 2581.09     140 2569.69   158.4 2560.52   170.2 2550.81   173.2 2549.38
   202.3 2547.94   233.6 2547.61   250.7  2546.1   275.9 2547.49   294.6 2545.05
   303.4 2543.19     321 2546.05   334.2 2544.41   351.4 2543.47   354.4 2544.51
   356.2 2545.94   364.9 2557.62   369.3 2562.19   381.6 2573.85   391.3 2581.54
   404.5 2590.01   420.8 2598.55   426.9 2600.93     439 2608.59     466  2622.4
#Mann= 5 ,-1,0
       0      .1       0     140     .06       0   250.7      .1       0
   334.2    .045       0   354.4      .1       0
#XS Ineff= 2 , 0
           272.7    2550
Permanent Ineff=
       F       F
Bank Sta=334.2,354.4
XS Rating Curve= 0 ,0
Exp/Cntr(USF)=0,0
Exp/Cntr=0.3,0.1

Type RM Length L Ch R = 1 ,10158   ,320.5,326.2,331.7
XS GIS Cut Line= 2
2173024.42712663415069.8523421052172724.01930211414777.731629987
#Sta/Elev= 30
       0 2630.79    18.2 2621.76    34.6 2611.98    58.3 2599.28    72.9 2592.34
      84 2585.59   111.9  2570.8   150.6 2552.21   159.1 2545.77   161.6 2544.89
   178.9 2544.94   221.3 2542.61   236.2  2543.2   240.3 2542.41   243.9 2540.23
   249.6 2539.31   263.7 2540.21     275 2541.93   297.7 2540.72     309 2541.38
   316.5 2540.78   320.3  2541.7     326 2545.05   345.2 2559.23   357.4 2566.01
   371.2 2572.69   385.3 2582.02   402.1 2588.56   413.2    2596     419 2601.51
#Mann= 5 ,-1,0
       0      .1       0      60     .06       0     200      .1       0
   243.9    .045       0   263.7      .1       0
#XS Ineff= 2 , 0
          235.78 2544.19
Permanent Ineff=
       F       F
Bank Sta=243.9,263.7
XS Rating Curve= 0 ,0
Exp/Cntr(USF)=0,0
Exp/Cntr=0.3,0.1

Type RM Length L Ch R = 1 ,9832    ,110.9,120.1,131.6
BEGIN DESCRIPTION:
structure xs 4
END DESCRIPTION:
XS GIS Cut Line= 2
2173183.95404034414891.6794254942172989.20689893 414512.54403317
#Sta/Elev= 30
       0 2603.49    10.6  2597.4    34.3 2585.18    52.3  2577.2    70.3 2570.86
    97.2 2558.28   119.7 2548.48   130.8 2544.85   138.4 2540.39   157.1 2539.96
   169.2 2537.71   212.6 2537.09   218.4 2534.98   223.2 2533.82   227.1 2533.78
   241.1 2533.81   245.6 2534.89   260.2 2539.03   268.1 2537.26   286.1 2536.22
   295.1 2535.05   298.8 2535.07   304.1 2536.06   323.4 2544.71   340.1 2547.98
   358.2 2554.82     376 2558.87   393.8 2567.56   411.7 2574.83   426.2 2579.78
#Mann= 4 ,-1,0
       0      .1       0     130     .06       0   218.4    .045       0
   245.6      .1       0
#XS Ineff= 2 ,-1
     100     200 2539.96  260.56  332.11 2539.96
Permanent Ineff=
       F       F
Bank Sta=218.4,245.6
XS Rating Curve= 0 ,0
Exp/Cntr(USF)=0,0
Exp/Cntr=0.5,0.3

Type RM Length L Ch R = 1 ,9712    ,29,29.8,28.2
BEGIN DESCRIPTION:
structure xs 3; 7.1 ft between structure and xs
END DESCRIPTION:
XS GIS Cut Line= 4
2173248.21421613414839.7461435712173184.64439279414664.929129373
 2173221.6475368414447.4693638332173090.20634774414382.072991484
#Sta/Elev= 30
       0 2598.66      27 2587.47    62.3 2575.75    75.1 2570.73    96.4 2560.13
   111.3 2553.74   134.7 2544.83   145.6  2538.5   148.7  2537.9   161.2 2538.65
     186 2537.69   193.9 2536.33     202 2532.31   222.3 2531.33224.20992532.234
   230.4 2536.23   234.5 2537.78   311.5 2532.95   368.4 2532.29   408.2 2530.34
   433.3 2530.86   456.6 2529.87   463.1 2529.21   466.1 2529.41   470.8    2531
   502.1 2548.57   516.8 2558.14   528.9 2563.34   542.3  2570.8   553.4 2575.25
#Mann= 7 ,-1,0
       0      .1       0      70     .06       0     202    .045       0
224.2099     .06       0  276.02      .1       0  376.02     .06       0
   456.6      .1       0
#XS Ineff= 3 ,-1
       0     195  2535.5     231  234.93  2534.5  234.93     550    2540
Permanent Ineff=
       F       F       F
Bank Sta=202,224.2099
XS Rating Curve= 0 ,0
Exp/Cntr(USF)=0,0
Exp/Cntr=0.5,0.3

Type RM Length L Ch R = 1 ,9682    ,334.9,306.3,285.9
BEGIN DESCRIPTION:
structure xs 2; 7.5 ft between structure and xs
END DESCRIPTION:
XS GIS Cut Line= 4
2173277.10959038414834.6894530772173213.53976704414659.872438879
2173253.38444131414411.1558404122173099.21101012414363.755826416
#Sta/Elev= 30
       0 2608.86    17.5 2601.78    52.7 2589.79    65.5  2584.9    92.4  2570.7
   103.8 2566.84   150.6 2545.15   163.3 2537.46   167.6 2536.88   188.7 2537.69
   192.8 2536.11   196.8 2533.28   200.9 2532.06     215 2531.01221.35752532.027
   225.2  2537.4   229.5 2537.54   298.1 2533.76   326.8  2532.7   419.7 2530.61
   459.7 2530.63   501.9 2529.03   510.9 2529.42   514.5 2530.25   517.3 2531.51
   527.1 2536.92   539.6 2544.61   552.2 2550.83   585.6 2569.81   599.2  2576.4
#Mann= 7 ,-1,0
       0      .1       0      70     .06       0   200.9    .045       0
221.3575     .06       0  276.02      .1       0  376.02     .06       0
   517.9      .1       0
#XS Ineff= 3 ,-1
       0   197.5  2534.2   223.8  230.42  2534.1  230.42     550 2538.34
Permanent Ineff=
       F       F       F
Bank Sta=200.9,221.3575
XS Rating Curve= 0 ,0
Exp/Cntr(USF)=0,0
Exp/Cntr=0.5,0.3

Type RM Length L Ch R = 1 ,9376    ,27.4,26.2,26.1
BEGIN DESCRIPTION:
structure xs 1
END DESCRIPTION:
XS GIS Cut Line= 3
2173553.86609086414520.4025583992173434.87287834414418.675130349
2173103.27480205414359.584566103
#Sta/Elev= 30
       0 2630.46    48.1 2605.82    60.2 2593.86    82.9 2581.45   109.6 2564.95
   122.6  2558.4   146.5  2548.8   175.5 2542.51   191.8 2536.51   199.9 2531.21
     208 2527.97   212.1 2526.46   220.2  2527.5   232.6 2526.55   236.5 2527.05
  238.29 2528.06   244.6 2531.44   248.7 2532.32   264.9 2530.22   285.2 2529.85
   362.4 2530.42     399 2529.12   407.1 2529.78   415.3 2533.39   423.4 2538.58
   447.8 2552.35     464 2560.44   472.1 2563.82   484.3 2571.66   493.4 2575.84
#Mann= 5 ,-1,0
       0      .1       0     208    .045       0  238.29      .1       0
  326.55     .06       0  426.55      .1       0
#XS Ineff= 2 , 0
                          248.73         2543.97
Permanent Ineff=
       F       F
Bank Sta=208,238.29
XS Rating Curve= 0 ,0
Exp/Cntr(USF)=0,0
Exp/Cntr=0.3,0.1

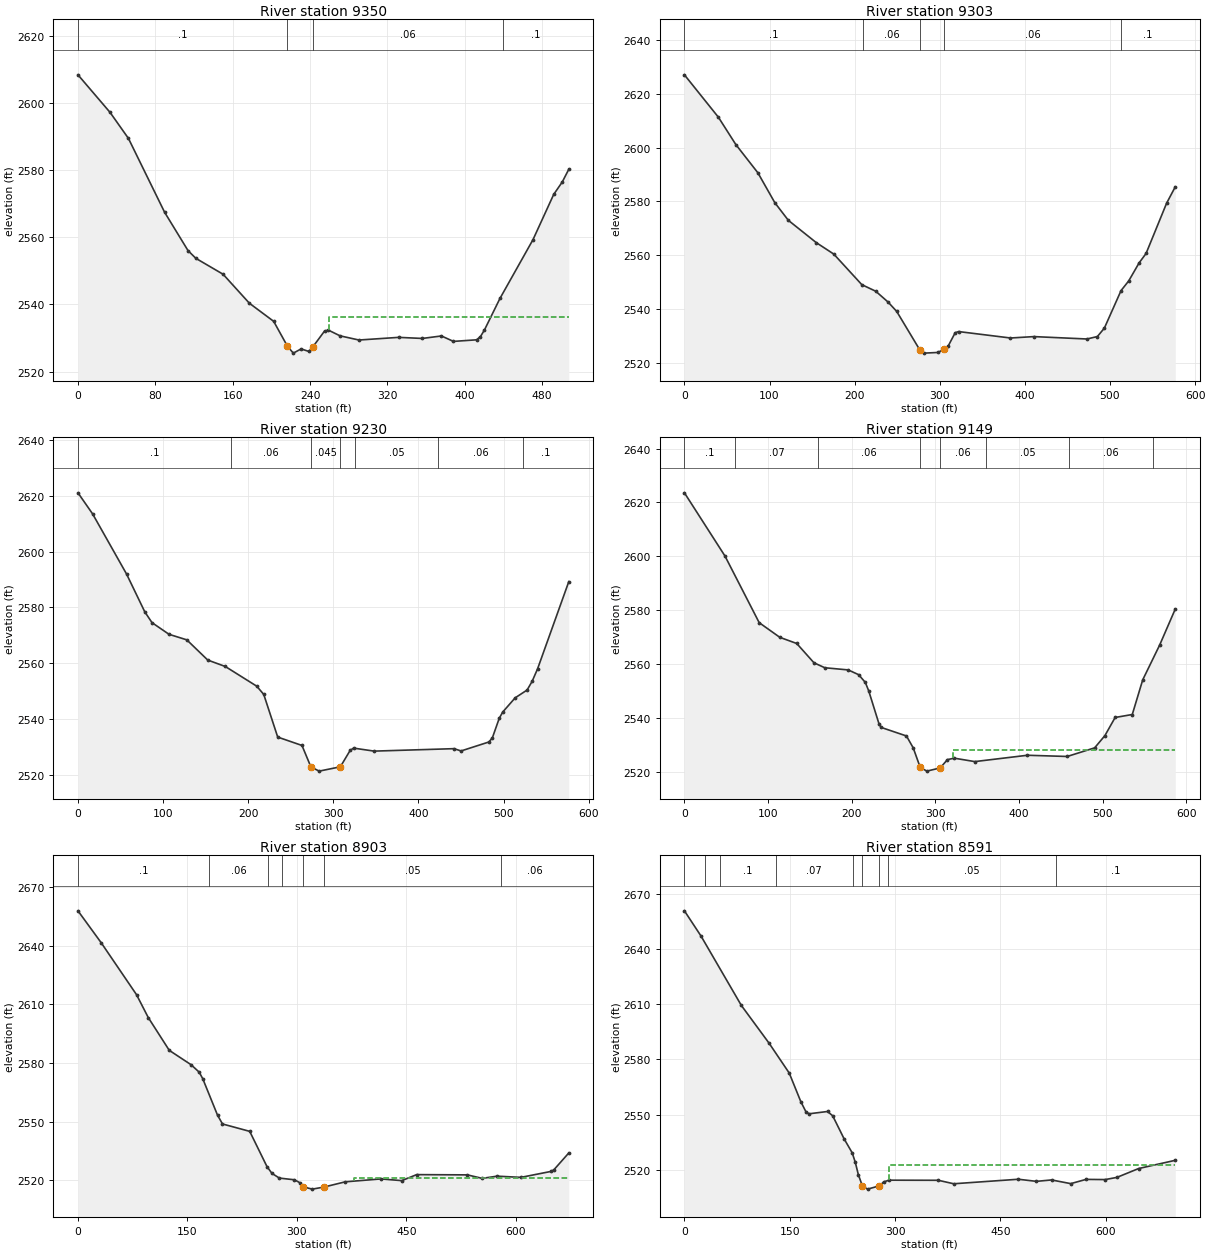
Type RM Length L Ch R = 1 ,9350    ,53.4,46.2,42.2
BEGIN DESCRIPTION:
structure xs 4
END DESCRIPTION:
XS GIS Cut Line= 2
2173605.07208809414410.6498359932173101.57019183414346.357628292
#Sta/Elev= 30
       0 2608.32    33.2 2597.14    52.2  2589.4    89.6 2567.43   113.8 2556.03
   121.9 2553.72   150.1 2548.98   177.3 2540.35   202.4 2534.97   216.6 2527.58
   222.7 2525.51   230.8 2526.76   238.8 2526.01   242.9 2527.37     255 2532.07
     259 2532.35   271.1 2530.65   290.6 2529.41   331.6  2530.2   356.1 2529.88
   375.9 2530.62   388.3    2529   412.2 2529.47   416.2 2530.41   420.3 2532.36
   436.4 2541.78   470.6 2559.29     492 2572.74   500.9 2576.46   507.6 2580.22
#Mann= 4 ,-1,0
       0      .1       0   216.6    .045       0   242.9     .06       0
     440      .1       0
#XS Ineff= 2 , 0
                          259.61         2536.27
Permanent Ineff=
       F       F
Bank Sta=216.6,242.9
XS Rating Curve= 0 ,0
Exp/Cntr(USF)=0,0
Exp/Cntr=0.5,0.3

Type RM Length L Ch R = 1 ,9303    ,64.6,73.6,69.8
BEGIN DESCRIPTION:
structure xs 3; 8.8 ft between structure and xs
END DESCRIPTION:
XS GIS Cut Line= 4
2173674.96545007414386.1655690622173436.03414874  414329.7427881
2173329.84364838 414344.912859582173110.58343212414299.463484967
#Sta/Elev= 30
       0 2627.03    39.9 2611.29    60.4 2601.13    86.3 2590.64   106.2 2579.54
   122.1 2572.98   154.9  2564.7   175.5 2560.44   208.4 2549.09   224.8 2546.64
   239.2 2542.64   249.4 2539.15   276.7 2524.77   281.7 2523.65   297.9  2523.9
     305 2525.07     310 2526.35   318.1 2531.21   322.1 2531.66   383.1 2529.27
   410.6 2529.79   472.9  2528.9   485.2 2529.81   493.4 2532.94     513 2546.88
     522 2550.47   534.2 2557.16   542.4 2560.67   566.5 2579.32   576.7 2585.43
#Mann= 5 ,-1,0
       0      .1       0     210     .06       0   276.7    .045       0
     305     .06       0  512.77      .1       0
#XS Ineff= 2 , 0
           267.7  2525.6     314          2527.1
Permanent Ineff=
       F       F
Bank Sta=276.7,305
XS Rating Curve= 0 ,0
Exp/Cntr(USF)=0,0
Exp/Cntr=0.5,0.3

Type RM Length L Ch R = 1 ,9230    ,70.1,80.7,87.5
BEGIN DESCRIPTION:
structure xs 2; 18.5 ft between structure and xs
END DESCRIPTION:
XS GIS Cut Line= 4
2173688.60739911414325.4164626392173449.67609779414268.993681677
2173343.48559743414284.1637531572173124.22538117414238.714378544
#Sta/Elev= 30
       0 2621.08    17.2 2613.54    57.1 2591.98    78.5 2578.44      87 2574.56
     107 2570.38   127.9 2568.39   152.5 2561.15   173.1 2558.85   210.1 2551.78
   218.3 2548.83   234.7 2533.55   263.2 2530.55  273.672522.868   283.4 2521.35
   308.3  2522.9   319.8 2528.78   323.8  2529.6     348 2528.52   441.9  2529.4
   450.1 2528.58   482.8 2531.79   486.9 2533.28     495  2540.3   499.1 2542.54
   513.7 2547.62   527.7 2550.41   533.6 2553.51     540 2557.99   576.7 2589.26
#Mann= 7 ,-1,0
       0      .1       0     180     .06       0  273.67    .045       0
   308.3     .06       0   325.5     .05       0  422.77     .06       0
  522.77      .1       0
#XS Ineff= 2 , 0
           266.7  2524.6     314          2525.7
Permanent Ineff=
       F       F
Bank Sta=273.67,308.3
XS Rating Curve= 0 ,0
Exp/Cntr(USF)=0,0
Exp/Cntr=0.5,0.3

Type RM Length L Ch R = 1 ,9149    ,246.5,245.9,245.3
BEGIN DESCRIPTION:
structure xs 1
END DESCRIPTION:
XS GIS Cut Line= 2
2173723.54312251414265.4505803992173149.96994369414141.200471134
#Sta/Elev= 30
       0 2623.58    48.5 2600.11    89.4 2575.37   114.1 2569.92   134.3 2567.64
   154.9 2560.47   167.9 2558.63   195.8 2557.83   208.3 2556.06   216.3 2553.19
   220.4 2550.02   232.6 2537.86   235.2 2536.48   265.5  2533.3   273.6 2528.86
   281.9 2521.65   289.9 2520.25   305.8 2521.44   314.5 2524.52   322.6 2525.06
   347.2 2523.79   410.1 2526.14   457.7 2525.69   490.5 2528.89   502.8 2533.45
     515 2540.17   535.5 2541.27     548 2554.15   568.3  2567.1   586.9 2580.43
#Mann= 8 ,-1,0
       0      .1       0      60     .07       0     160     .06       0
   281.9    .045       0   305.8     .06       0     360     .05       0
     460     .06       0     560      .1       0
#XS Ineff= 2 , 0
                          321.46         2528.25
Permanent Ineff=
       F       F
Bank Sta=281.9,305.8
XS Rating Curve= 0 ,0
Exp/Cntr(USF)=0,0
Exp/Cntr=0.3,0.1

Type RM Length L Ch R = 1 ,8903    ,307.7,312.4,315.5
XS GIS Cut Line= 2
2173842.77947618 414040.178626342173183.95404034413905.513049832
#Sta/Elev= 30
       0 2657.75    31.9 2641.41    80.2 2614.93    96.3 2603.23   125.1 2586.46
   154.8 2579.17     166 2575.36   170.9 2572.03   191.2 2553.35     198 2548.86
   235.3 2545.08     259 2527.04   265.8  2523.6   275.9 2521.21   296.6 2520.34
   304.8 2518.67   308.9 2516.68   321.1 2515.57   337.4 2516.66     366 2519.29
     415 2520.78   443.6 2519.91     464 2522.98   533.4 2522.85   553.8 2521.07
   574.2 2522.19   606.9 2521.58   647.7 2524.59   651.8 2525.38   672.4 2534.05
#Mann= 7 ,-1,0
       0      .1       0     180     .06       0     260      .1       0
     280     .05       0   308.9    .045       0   337.4     .05       0
     580     .06       0
#XS Ineff= 2 , 0
                             378         2521.48
Permanent Ineff=
       F       F
Bank Sta=308.9,337.4
XS Rating Curve= 0 ,0
Exp/Cntr(USF)=0,0
Exp/Cntr=0.3,0.1

Type RM Length L Ch R = 1 ,8591    ,216.3,218.4,220.9
XS GIS Cut Line= 2
2173886.28681628413810.2112572262173248.17916144413524.305879408
#Sta/Elev= 30
       0 2660.93    23.6 2647.22    81.1 2609.41   120.7 2588.81   149.3 2572.61
   165.8 2557.05   173.3 2551.37   177.6 2550.44   203.9 2551.69   211.2 2549.35
   227.5 2536.77     239 2529.18   243.4 2524.01   247.8 2517.22   253.6 2511.07
   260.9 2509.42   277.8 2511.21   283.9 2513.38   291.6 2514.29   361.7 2514.23
   383.6 2512.34   475.7  2514.8   501.4 2513.65     523 2514.42   550.3 2512.41
   572.1 2514.72   599.3 2514.62     616  2515.8   647.1 2520.64   699.2 2525.11
#Mann= 9 ,-1,0
       0      .1       0      30     .06       0      50      .1       0
     130     .07       0     240      .1       0   253.6    .045       0
   277.8      .1       0     290     .05       0     530      .1       0
#XS Ineff= 2 , 0
                          291.83          2522.6
Permanent Ineff=
       F       F
Bank Sta=253.6,277.8
XS Rating Curve= 0 ,0
Exp/Cntr(USF)=0,0
Exp/Cntr=0.3,0.1