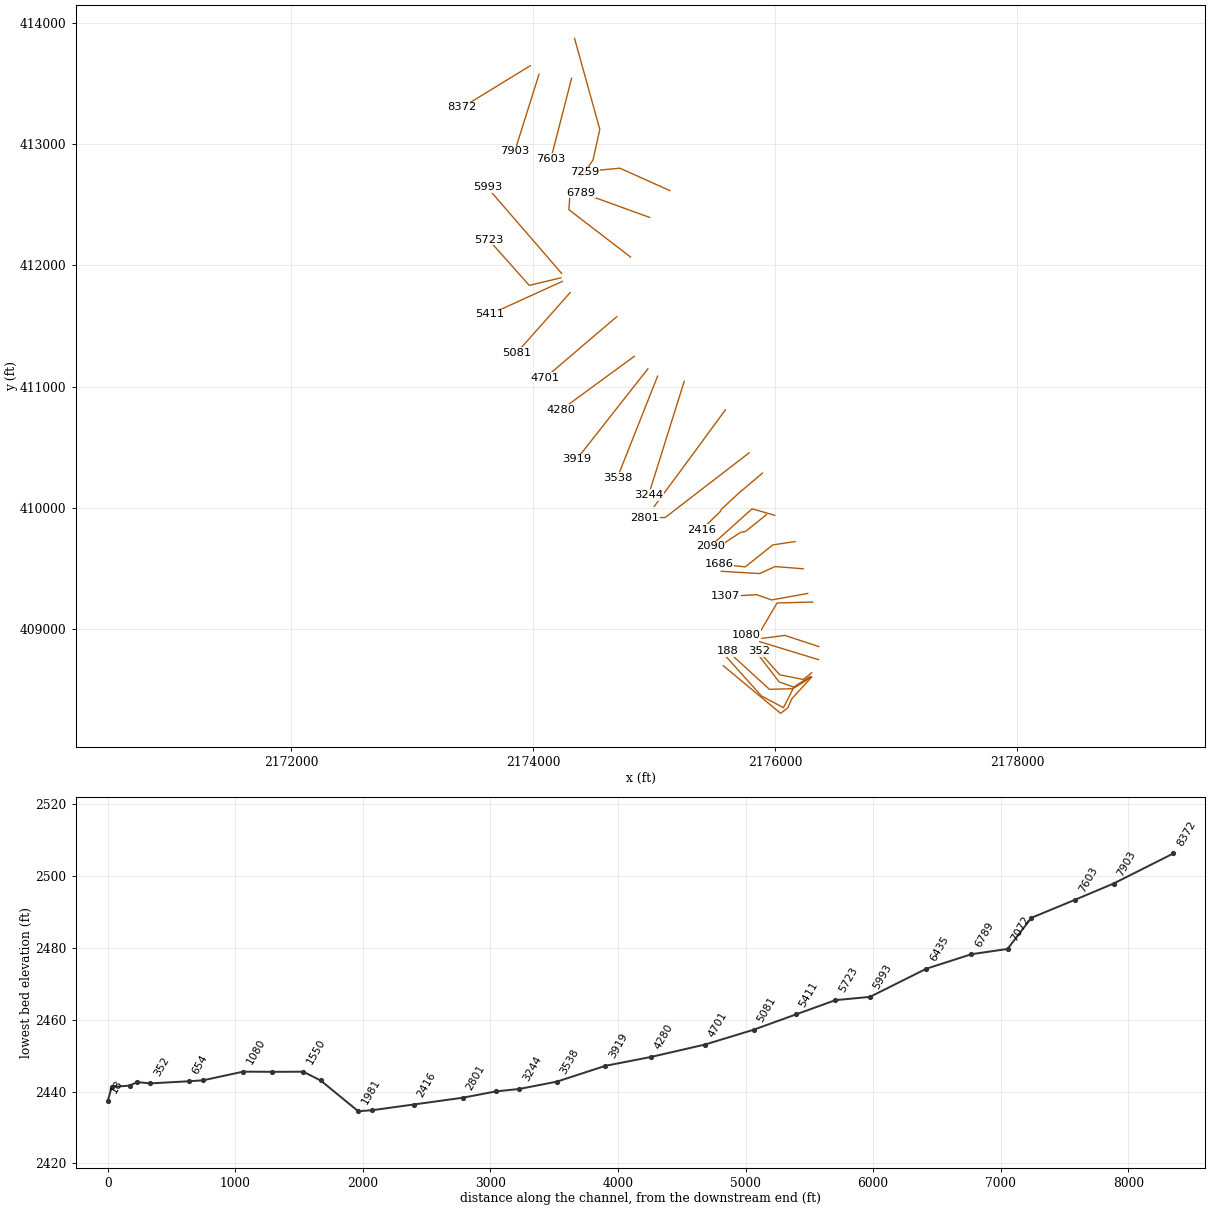
HEC-RAS study BRFFYCK.prj: BRFFYCK

--- BRFFYCK.g01 (geometry) --- (continued)

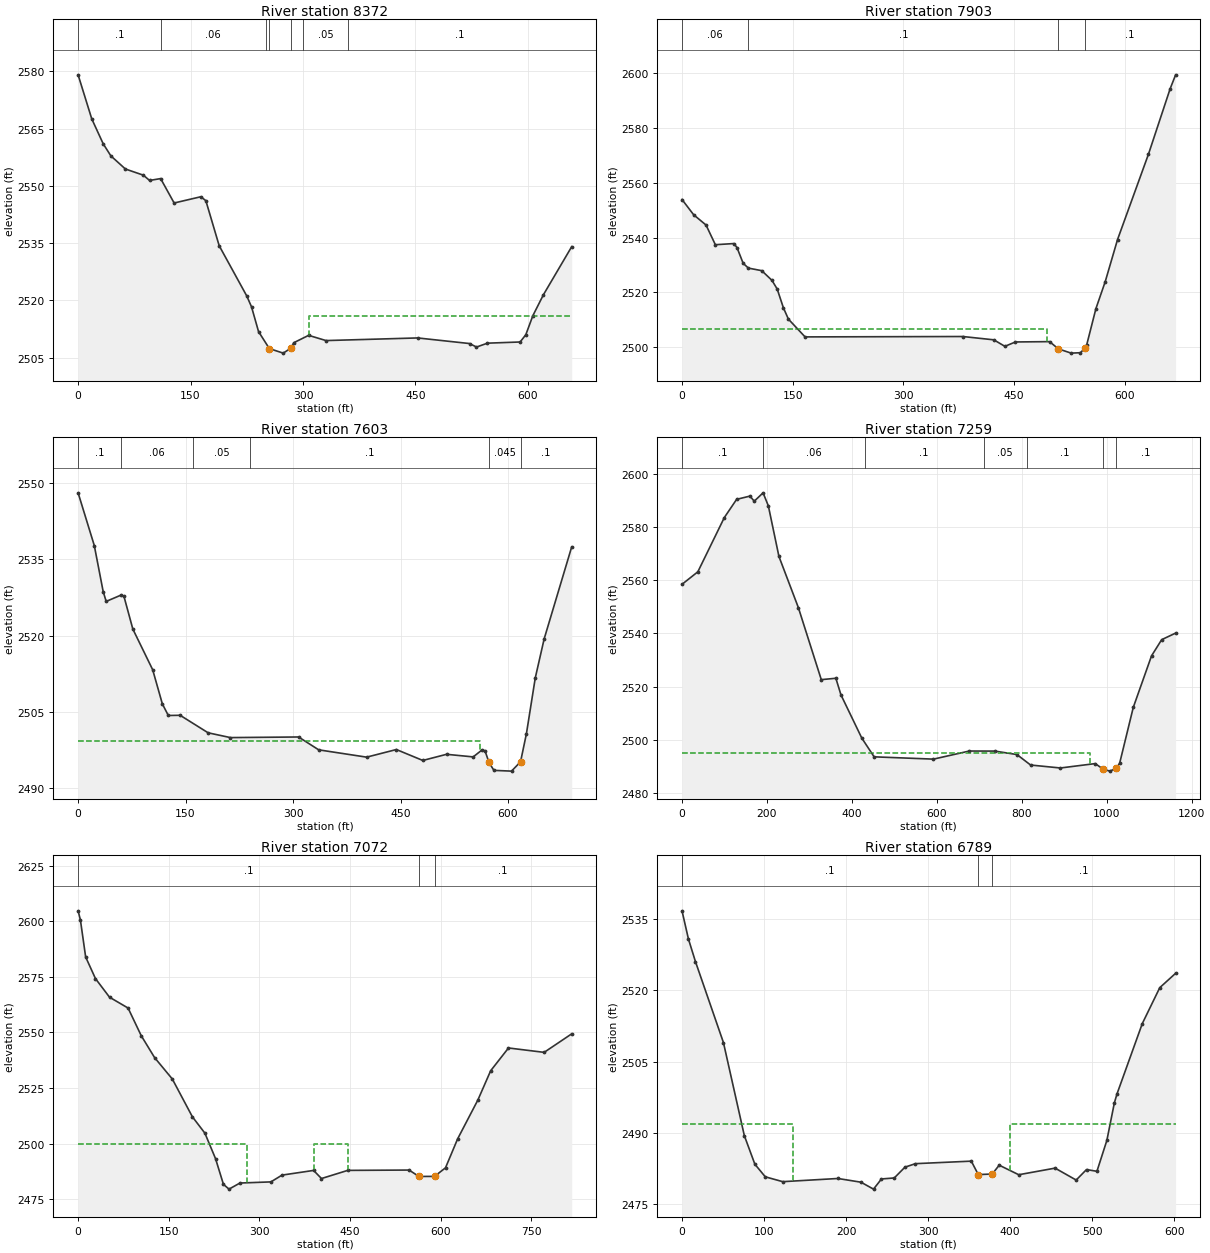
Type RM Length L Ch R = 1 ,8372    ,456.5,469.2,490.9
XS GIS Cut Line= 2
2173977.44505269413650.6843435152173415.99318755413306.769178894
#Sta/Elev= 30
       0 2579.09    18.2 2567.56    33.5 2561.01    43.7 2557.85    63.1 2554.41
    87.1 2552.79    95.3 2551.41   110.1  2551.9   128.1  2545.5   163.7 2547.14
   170.4 2546.11   188.2  2534.3     225 2521.13   231.3  2518.3   240.7  2511.8
   255.1 2507.35   273.6 2506.16   284.2 2507.51   287.6 2508.88   307.5 2510.82
   330.7 2509.45   452.9 2510.14   522.2 2508.67   531.4 2507.75     546 2508.77
   589.6 2509.08   597.2 2510.99   606.6 2515.98   620.7 2521.47   658.4 2534.06
#Mann= 7 ,-1,0
       0      .1       0     110     .06       0     250      .1       0
   255.1    .045       0   284.2      .1       0     300     .05       0
     360      .1       0
#XS Ineff= 2 , 0
                          308.39         2515.81
Permanent Ineff=
       F       F
Bank Sta=255.1,284.2
XS Rating Curve= 0 ,0
Exp/Cntr(USF)=0,0
Exp/Cntr=0.3,0.1

Type RM Length L Ch R = 1 ,7903    ,298.1,299.9,301.3
XS GIS Cut Line= 2
2174049.95728619413580.2438881112173848.99481048412942.136233271
#Sta/Elev= 30
       0 2553.93    15.8 2548.35    32.6 2544.59    45.2 2537.41    70.3 2537.83
    74.5 2536.38    82.9 2530.61      90 2528.86   108.1 2527.92   121.9 2524.39
     129 2521.22   137.4 2514.37   144.2 2510.22   166.8 2503.72   380.6 2503.86
   422.6 2502.65   437.6 2500.27   451.9 2501.87   498.2 2501.99   510.1 2499.34
   527.4 2497.79     540 2497.94     546 2499.59   548.4 2500.71     561 2514.07
   573.6 2523.91   590.3  2539.3   632.2 2570.48   661.6 2594.41     669 2599.49
#Mann= 4 ,-1,0
       0     .06       0      90      .1       0   510.1    .045       0
     546      .1       0
#XS Ineff= 2 , 0
          494.54 2506.46
Permanent Ineff=
       F       F
Bank Sta=510.1,546
XS Rating Curve= 0 ,0
Exp/Cntr(USF)=0,0
Exp/Cntr=0.3,0.1

Type RM Length L Ch R = 1 ,7603    ,343.6,344.5,345
XS GIS Cut Line= 2
2174319.28843921413547.095438509 2174147.3308569412879.982890267
#Sta/Elev= 30
       0 2548.08    22.6 2537.71      35 2528.65    39.2 2526.71      60 2527.96
    63.9 2527.75    76.4 2521.27   104.1 2513.26   117.6 2506.54   125.9 2504.26
   142.4  2504.3   181.5 2500.85   212.6 2499.91   307.7 2500.03   335.8  2497.5
   402.7 2496.06   444.2 2497.56   481.1 2495.41   514.2 2496.62   551.4 2496.11
   563.8 2497.49   567.9 2497.31   573.4 2495.04   580.3 2493.46   604.9 2493.31
   617.5 2495.15   625.7 2500.68   638.1 2511.69   650.5 2519.36   688.9 2537.45
#Mann= 6 ,-1,0
       0      .1       0      60     .06       0     160     .05       0
     240      .1       0   573.4    .045       0   617.5      .1       0
#XS Ineff= 2 , 0
          561.18 2499.24
Permanent Ineff=
       F       F
Bank Sta=573.4,617.5
XS Rating Curve= 0 ,0
Exp/Cntr(USF)=0,0
Exp/Cntr=0.3,0.1

Type RM Length L Ch R = 1 ,7259    ,206.2,187.1,155.9
XS GIS Cut Line= 4
2174343.34417438413877.1111075442174552.14394764413124.415279941
2174496.16207358412873.1365298942174428.56775478412769.687232019
#Sta/Elev= 30
       0 2558.44    37.3 2563.15    99.6 2583.52   128.6 2590.37   159.9 2591.59
   170.1 2589.68   190.9 2592.82   203.3 2587.91   228.2 2568.92   273.9 2549.72
   327.9 2522.63   362.2 2523.15   374.3 2516.88   423.3 2500.67   452.3 2493.63
     592 2492.77   676.5 2495.81   736.3 2495.79   788.5 2494.49   820.7 2490.55
   890.9 2489.44   972.9 2491.09990.21362489.139  1006.9 2488.261022.4732489.266
  1030.3  2491.2  1062.4 2512.19  1105.4 2531.57  1129.3 2537.65  1162.1 2540.12
#Mann= 7 ,-1,0
       0      .1       0     190     .06       0     430      .1       0
     710     .05       0  811.12      .1       0990.2136    .045       0
1022.473      .1       0
#XS Ineff= 2 , 0
          961.46  2495.2
Permanent Ineff=
       F       F
Bank Sta=990.2136,1022.473
XS Rating Curve= 0 ,0
Exp/Cntr(USF)=0,0
Exp/Cntr=0.3,0.1

Type RM Length L Ch R = 1 ,7072    ,282.8,282.7,270.9
XS GIS Cut Line= 4
 2175131.6156535 412618.62737544 2174717.7916476412804.241144493
2174541.08926251 412787.350475332174364.88770276412729.041887297
#Sta/Elev= 30
       0 2604.65     3.8 2600.59    12.5 2583.92    28.7 2574.22      52 2565.84
    82.7 2560.97   104.4 2548.58   126.5 2538.73   155.9 2529.08   189.1 2512.11
   209.8 2504.75   227.4 2493.31   240.5 2481.75   249.7 2479.61   267.8 2482.35
     319 2482.86   337.4 2485.91   389.6 2488.01   402.7 2484.37   446.1 2488.03
   547.6 2488.18563.90692485.302   589.7 2485.33   607.9 2489.19     628 2502.22
   661.5 2519.68   682.6 2532.79   712.1 2543.03   771.1 2541.06   816.7 2549.38
#Mann= 3 ,-1,0
       0      .1       0563.9069    .045       0   589.7      .1       0
#XS Ineff= 2 ,-1
       0     280    2500   389.6   446.1    2500
Permanent Ineff=
       F       F
Bank Sta=563.9069,589.7
XS Rating Curve= 0 ,0
Exp/Cntr(USF)=0,0
Exp/Cntr=0.3,0.1

Type RM Length L Ch R = 1 ,6789    ,359.6,353.8,347.3
XS GIS Cut Line= 2
2174963.61142835412397.2585929362174398.01600702412602.364624849
#Sta/Elev= 30
       0 2536.73     7.9 2530.76    16.4 2526.04    50.5    2509      76 2489.39
    88.8  2483.4   101.5 2480.74   122.8 2479.72     190 2480.39   218.1 2479.61
   233.4 2478.15   243.1 2480.29   258.7  2480.5   271.7 2482.77   284.5 2483.51
   352.6 2484.04   361.1 2481.21   378.1 2481.33   386.6 2483.19   410.4 2481.18
   454.7 2482.57   480.4 2480.06     493 2482.27   505.7  2481.9   517.8  2488.4
     527 2496.34   530.3 2498.26     561    2513   582.3 2520.56   601.6 2523.58
#Mann= 3 ,-1,0
       0      .1       0   361.1    .045       0   378.1      .1       0
#XS Ineff= 2 , 0
          135.48 2491.88     400         2491.88
Permanent Ineff=
       F       F
Bank Sta=361.1,378.1
XS Rating Curve= 0 ,0
Exp/Cntr(USF)=0,0
Exp/Cntr=0.3,0.1

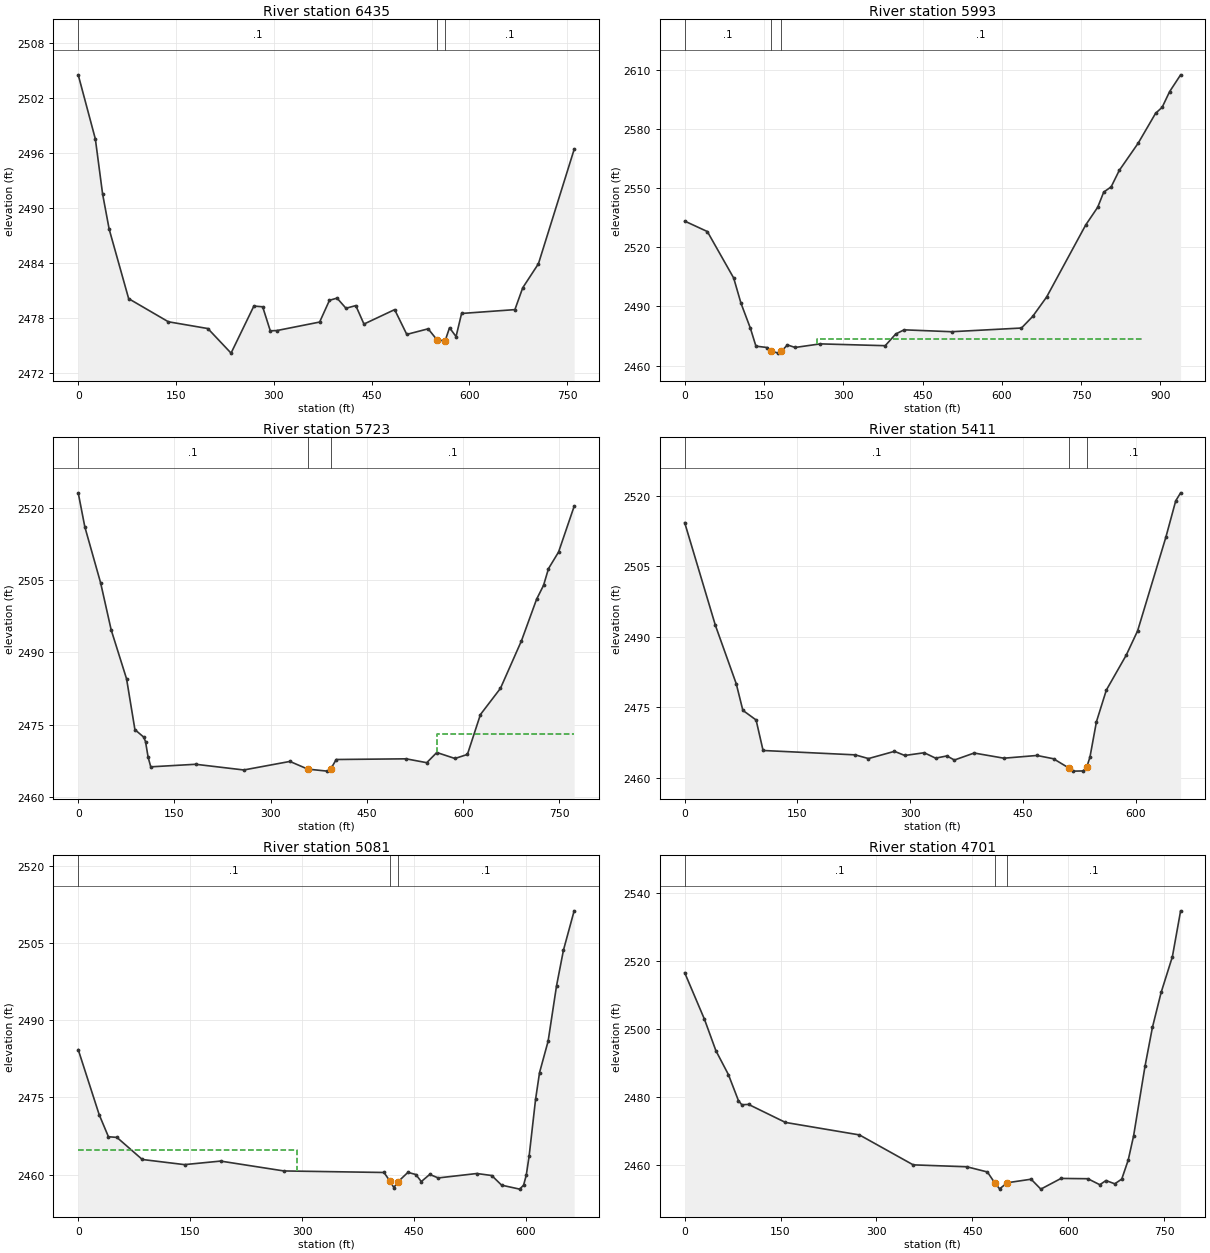
Type RM Length L Ch R = 1 ,6435    ,444.9,442.3,438.4
XS GIS Cut Line= 3
2174805.85440836412070.0187690522174296.82420076412461.230632252
2174304.37419517412579.903776498
#Sta/Elev= 30
       0 2504.57    26.3 2497.55    37.4 2491.54    47.5 2487.68    77.4 2480.08
   138.3 2477.55   198.9 2476.81   234.5 2474.12   269.5 2479.27     283 2479.19
   294.7 2476.56   304.8 2476.59   370.4 2477.52   385.5  2479.9   397.1 2480.14
   410.8 2479.03   425.9 2479.32   438.4  2477.3   485.5 2478.88   504.1 2476.17
   536.9 2476.78   551.1 2475.52   563.1  2475.5   569.7  2476.9   579.7 2475.93
   588.2 2478.46     670 2478.88     682 2481.27   706.1  2483.9   760.9 2496.41
#Mann= 3 ,-1,0
       0      .1       0   551.1    .045       0   563.1      .1       0
Bank Sta=551.1,563.1
XS Rating Curve= 0 ,0
Exp/Cntr(USF)=0,0
Exp/Cntr=0.3,0.1

Type RM Length L Ch R = 1 ,5993    ,269.8,270,272.3
XS GIS Cut Line= 2
2174236.23939091411935.0741523042173622.72271406412645.039721858
#Sta/Elev= 30
       0  2533.4    42.9 2528.08    92.7 2504.47   106.5 2491.67   124.4 2478.88
   134.8 2469.84   156.1 2469.14   163.2 2467.37   177.2 2466.29     183 2467.27
   194.4 2470.45     209 2469.17   256.5 2470.99   379.4 2470.07   399.3    2476
   415.1 2478.13     505 2477.17   637.2 2479.05   658.3 2484.91   684.8 2494.81
   758.7 2531.41   781.4 2540.42   792.8 2548.12   806.9 2550.81   822.2 2559.15
     858 2572.99   890.9 2588.16   903.4 2591.25   917.5  2599.2   938.3 2607.73
#Mann= 3 ,-1,0
       0      .1       0   163.2    .045       0     183      .1       0
#XS Ineff= 1 ,-1
     250   867.32473.326
Permanent Ineff=
       F
Bank Sta=163.2,183
XS Rating Curve= 0 ,0
Exp/Cntr(USF)=0,0
Exp/Cntr=0.3,0.1

Type RM Length L Ch R = 1 ,5723    ,291.9,311.6,338.1
XS GIS Cut Line= 3
2174230.20198091411897.9600708052173969.15794029411835.806727801
2173633.52988807412212.870342025
#Sta/Elev= 30
       0 2523.08    10.3 2516.03      35 2504.38    51.4 2494.66    75.4 2484.51
    88.4 2473.99     102 2472.45   104.9 2471.53     109 2468.26   113.1 2466.28
     183 2466.81   258.1 2465.63     330  2467.4   357.8 2465.81     388 2465.39
   393.3 2465.76   402.2  2467.8   511.2 2467.94   543.3 2467.14     559 2469.25
   587.3 2468.01   606.7 2468.85     627 2477.12   658.2 2482.55     691 2492.42
   714.6 2501.04   725.4  2503.9   733.1 2507.37   748.8 2510.81   773.1 2520.28
#Mann= 3 ,-1,0
       0      .1       0   357.8    .045       0   393.3      .1       0
#XS Ineff= 2 , 0
                          558.87         2472.99
Permanent Ineff=
       F       F
Bank Sta=357.8,393.3
XS Rating Curve= 0 ,0
Exp/Cntr(USF)=0,0
Exp/Cntr=0.3,0.1

Type RM Length L Ch R = 1 ,5411    ,323.7,330.6,338.8
XS GIS Cut Line= 2
2174242.63264951411868.9551774032173642.25321299411595.258046078
#Sta/Elev= 30
       0 2514.26    40.9 2492.39    68.6 2479.99    77.4 2474.33      95 2472.28
   104.3 2465.79   226.9 2464.86   244.5 2464.07   279.1 2465.61   292.8 2464.73
   318.7 2465.31   333.8 2464.16   348.9 2464.63   358.8 2463.76   385.1 2465.25
   424.7 2464.15   468.7 2464.73   490.7 2464.03   511.72462.005     517  2461.4
   530.2 2461.44     5352462.282   539.2  2464.4   547.8  2471.9     561 2478.65
   587.5 2486.09   602.6 2491.25   640.1 2511.12   653.3  2518.9   659.8  2520.6
#Mann= 3 ,-1,0
       0      .1       0   511.7    .045       0     535      .1       0
Bank Sta=511.7,535
XS Rating Curve= 0 ,0
Exp/Cntr(USF)=0,0
Exp/Cntr=0.3,0.1

Type RM Length L Ch R = 1 ,5081    ,381.9,379.7,376.2
XS GIS Cut Line= 2
2174306.85777061411775.7251628972173865.56903528411278.498418866
#Sta/Elev= 30
       0 2484.32    28.1 2471.66    40.5 2467.36    51.9 2467.23    85.9 2462.93
   142.5 2461.93   190.8 2462.62   275.7  2460.7   409.9  2460.4   417.4 2458.82
   423.1 2457.47   428.7 2458.59     442 2460.43   452.6    2460   459.9 2458.63
   471.2 2460.02   482.6 2459.34   534.3  2460.2   554.3 2459.81   567.6 2457.93
   591.7 2457.16     597 2457.92   600.6 2459.87   604.4 2463.54   613.1 2474.65
   618.4 2479.84   629.9 2485.96   641.2 2496.75   650.5 2503.71   664.8 2511.34
#Mann= 3 ,-1,0
       0      .1       0   417.4    .045       0   428.7      .1       0
#XS Ineff= 2 , 0
          293.55  2464.8
Permanent Ineff=
       F       F
Bank Sta=417.4,428.7
XS Rating Curve= 0 ,0
Exp/Cntr(USF)=0,0
Exp/Cntr=0.3,0.1

Type RM Length L Ch R = 1 ,4701    ,420.1,420.8,420.4
XS GIS Cut Line= 2
2174692.20849723411576.834465285 2174101.7517387411073.392386953
#Sta/Elev= 30
       0 2516.54      31 2502.85    48.8 2493.68    68.4 2486.66    84.1 2479.02
    89.4  2477.8    99.9 2477.91   157.7 2472.62   273.4 2468.96   357.5 2460.18
   441.6 2459.61   473.6 2458.09     485 2454.92   492.7 2453.14   504.7 2454.93
     542 2455.97   557.2 2453.06   588.8  2456.2   630.8 2456.11   649.5 2454.35
   659.1 2455.58   672.9 2454.62   683.8 2456.01   693.9 2461.57   702.3 2468.64
   720.2 2489.11   731.8  2500.5   745.4 2510.74     763 2521.21   775.9 2534.68
#Mann= 3 ,-1,0
       0      .1       0     485    .045       0   504.7      .1       0
Bank Sta=485,504.7
XS Rating Curve= 0 ,0
Exp/Cntr(USF)=0,0
Exp/Cntr=0.3,0.1

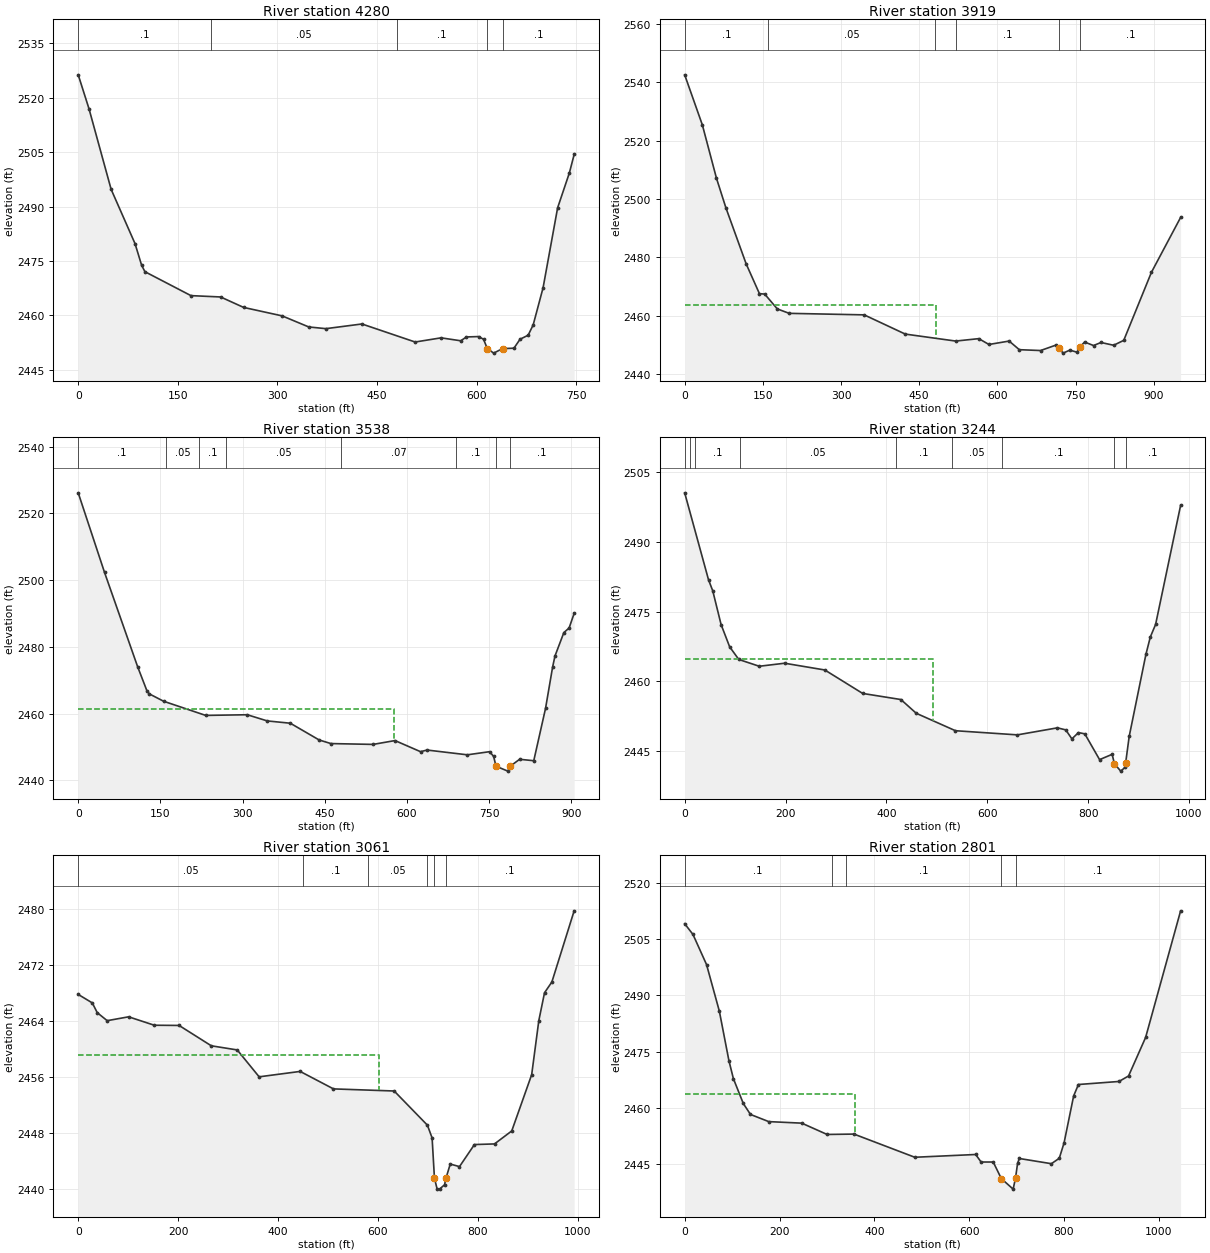
Type RM Length L Ch R = 1 ,4280    ,353.9,360.7,370.1
XS GIS Cut Line= 2
2174837.23296424411249.4935254642174234.34553711410808.204790136
#Sta/Elev= 30
       0 2526.29    16.2 2516.97    49.6 2494.74    85.6 2479.79    95.5 2473.85
   100.5 2472.06   169.8 2465.47   214.5  2465.1   249.2 2462.22   307.2 2459.89
   347.3 2456.84   373.1 2456.37   427.4 2457.66   507.6 2452.69   546.6 2453.84
   576.3 2453.03   584.9 2454.09   603.3 2454.19   610.6 2453.44   616.3 2450.87
   625.9 2449.63   639.2 2450.87   656.4 2450.99   665.6 2453.46   677.8 2454.56
   685.4 2457.42   700.3 2467.64   722.2 2489.66   739.9 2499.27   747.1 2504.35
#Mann= 5 ,-1,0
       0      .1       0     200     .05       0     480      .1       0
   616.3    .045       0   639.2      .1       0
Bank Sta=616.3,639.2
XS Rating Curve= 0 ,0
Exp/Cntr(USF)=0,0
Exp/Cntr=0.3,0.1

Type RM Length L Ch R = 1 ,3919    ,375.1,381.2,382.6
XS GIS Cut Line= 2
2174949.10898165411145.9046204582174360.72400121 410397.99272631
#Sta/Elev= 30
       0 2542.63    33.9 2525.45      61 2507.15    79.1    2497     118 2477.75
   143.4 2467.56   153.6 2467.39   177.8  2462.3   200.6 2460.79   344.4 2460.27
   423.3 2453.67     520 2451.28   564.3 2452.11   583.8 2450.11   622.6 2451.28
   642.1 2448.32   682.9 2448.03   713.4 2449.96   718.5 2448.85   726.1 2447.14
   738.9 2448.16   753.2 2447.45   758.42449.313   767.4 2450.94   784.5 2449.75
   798.8 2450.79   823.1 2449.84   842.5 2451.53   895.6 2474.87   951.6  2493.7
#Mann= 6 ,-1,0
       0      .1       0     160     .05       0     480     .07       0
     520      .1       0   718.5    .045       0   758.4      .1       0
#XS Ineff= 2 , 0
          482.33 2463.82
Permanent Ineff=
       F       F
Bank Sta=718.5,758.4
XS Rating Curve= 0 ,0
Exp/Cntr(USF)=0,0
Exp/Cntr=0.3,0.1

Type RM Length L Ch R = 1 ,3538    ,292.4,294.5,294.1
XS GIS Cut Line= 2
2175029.90832756411085.8230555542174696.35205344410244.681146901
#Sta/Elev= 30
       0 2526.16      48 2502.31   108.3 2474.09   125.5 2466.76   129.8 2465.89
   155.9 2463.68   232.6 2459.44   308.5 2459.64   344.9 2457.79     387  2457.1
   439.6 2452.08   461.1    2451     538 2450.75     578  2451.9   624.6 2448.57
   636.6 2449.06     710 2447.63   750.6 2448.57     758 2447.14   762.3 2444.22
   783.8 2442.74   788.1 2444.19   805.4 2446.29   831.2 2445.86   852.7 2461.55
   865.6 2473.94   869.9 2477.24   886.1 2484.27   895.7 2485.64   904.9 2490.04
#Mann= 8 ,-1,0
       0      .1       0     160     .05       0     220      .1       0
     270     .05       0     480     .07       0     690      .1       0
   762.3    .045       0   788.1      .1       0
#XS Ineff= 2 , 0
          576.34 2461.29
Permanent Ineff=
       F       F
Bank Sta=762.3,788.1
XS Rating Curve= 0 ,0
Exp/Cntr(USF)=0,0
Exp/Cntr=0.3,0.1

Type RM Length L Ch R = 1 ,3244    ,182.5,183.1,171.2
XS GIS Cut Line= 2
2175249.51680617411042.3157154512174955.32431595410103.800236092
#Sta/Elev= 30
       0  2500.5    47.3 2481.81    55.7 2479.44    72.2  2472.2    89.2 2467.41
   107.3  2464.7   147.9 2463.24   198.2 2463.89   277.9 2462.44     353  2457.4
   428.8 2456.09   459.2 2453.14     537 2449.39   659.8  2448.5   739.2 2450.01
   755.7 2449.57   767.9 2447.64   780.9 2448.99   793.5 2448.72   822.8 2443.18
   847.7 2444.32   852.2 2442.31   864.7 2440.71   873.1 2441.49  874.552442.524
   881.5 2448.16   914.7  2465.8   923.4 2469.52   933.9 2472.23   983.5 2497.81
#Mann= 9 ,-1,0
       0      .1       0      10     .05       0      20      .1       0
     110     .05       0     420      .1       0     530     .05       0
     630      .1       0   852.2    .045       0  874.55      .1       0
#XS Ineff= 2 , 0
          491.55 2464.83
Permanent Ineff=
       F       F
Bank Sta=852.2,874.55
XS Rating Curve= 0 ,0
Exp/Cntr(USF)=0,0
Exp/Cntr=0.3,0.1

Type RM Length L Ch R = 1 ,3061    ,250.5,259.4,245
XS GIS Cut Line= 3
2175590.39942573410807.9340474852175230.61127251410317.610615816
2175001.60008967410008.849234263
#Sta/Elev= 30
       0 2467.77    28.2 2466.56    38.1 2465.17      58 2464.03   100.9 2464.58
   152.3 2463.38   201.9 2463.35   266.4 2460.45   318.3 2459.86   362.1 2456.03
   444.2  2456.8   510.9 2454.31   632.4 2454.01   698.9 2449.14   708.3 2447.32
     713 2441.58   718.3 2440.06   723.2 2440.03   733.2 2440.65     736 2441.57
   744.6  2443.6   763.1 2443.24     793 2446.38   833.2 2446.47   867.7 2448.32
   907.6 2456.34   921.9 2464.05   933.3 2468.01     948 2469.54   992.6 2479.68
#Mann= 6 ,-1,0
       0     .05       0     450      .1       0     580     .05       0
  698.16      .1       0     713    .045       0     736      .1       0
#XS Ineff= 2 , 0
          601.13 2459.17
Permanent Ineff=
       F       F
Bank Sta=713,736
XS Rating Curve= 0 ,0
Exp/Cntr(USF)=0,0
Exp/Cntr=0.3,0.1

Type RM Length L Ch R = 1 ,2801    ,357.6,385.1,386.8
XS GIS Cut Line= 3
 2175786.1073341410451.8589569142175092.06167056 409917.34020708
2174922.17586635 409917.34020708
#Sta/Elev= 30
       0 2509.16    17.5 2506.29    46.1 2498.25    73.1 2485.81    93.3 2472.58
   102.7  2467.8   123.6 2461.15   138.8 2458.22   177.3 2456.31   246.9  2455.9
   300.3 2452.88     357 2452.98   485.3 2446.79   613.7 2447.53   625.1 2445.52
   650.7 2445.52   667.8 2441.09   692.7 2438.28  697.722441.232   702.1  2445.2
   705.8 2446.46   773.4 2445.07     790 2446.52   800.1 2450.63   820.3 2463.17
   830.4 2466.22   915.9 2467.03   936.1  2468.5   972.1 2478.79  1045.9  2512.6
#Mann= 5 ,-1,0
       0      .1       0     310     .05       0     340      .1       0
   667.8    .045       0  697.72      .1       0
#XS Ineff= 2 , 0
          359.45 2463.58
Permanent Ineff=
       F       F
Bank Sta=667.8,697.72
XS Rating Curve= 0 ,0
Exp/Cntr(USF)=0,0
Exp/Cntr=0.3,0.1

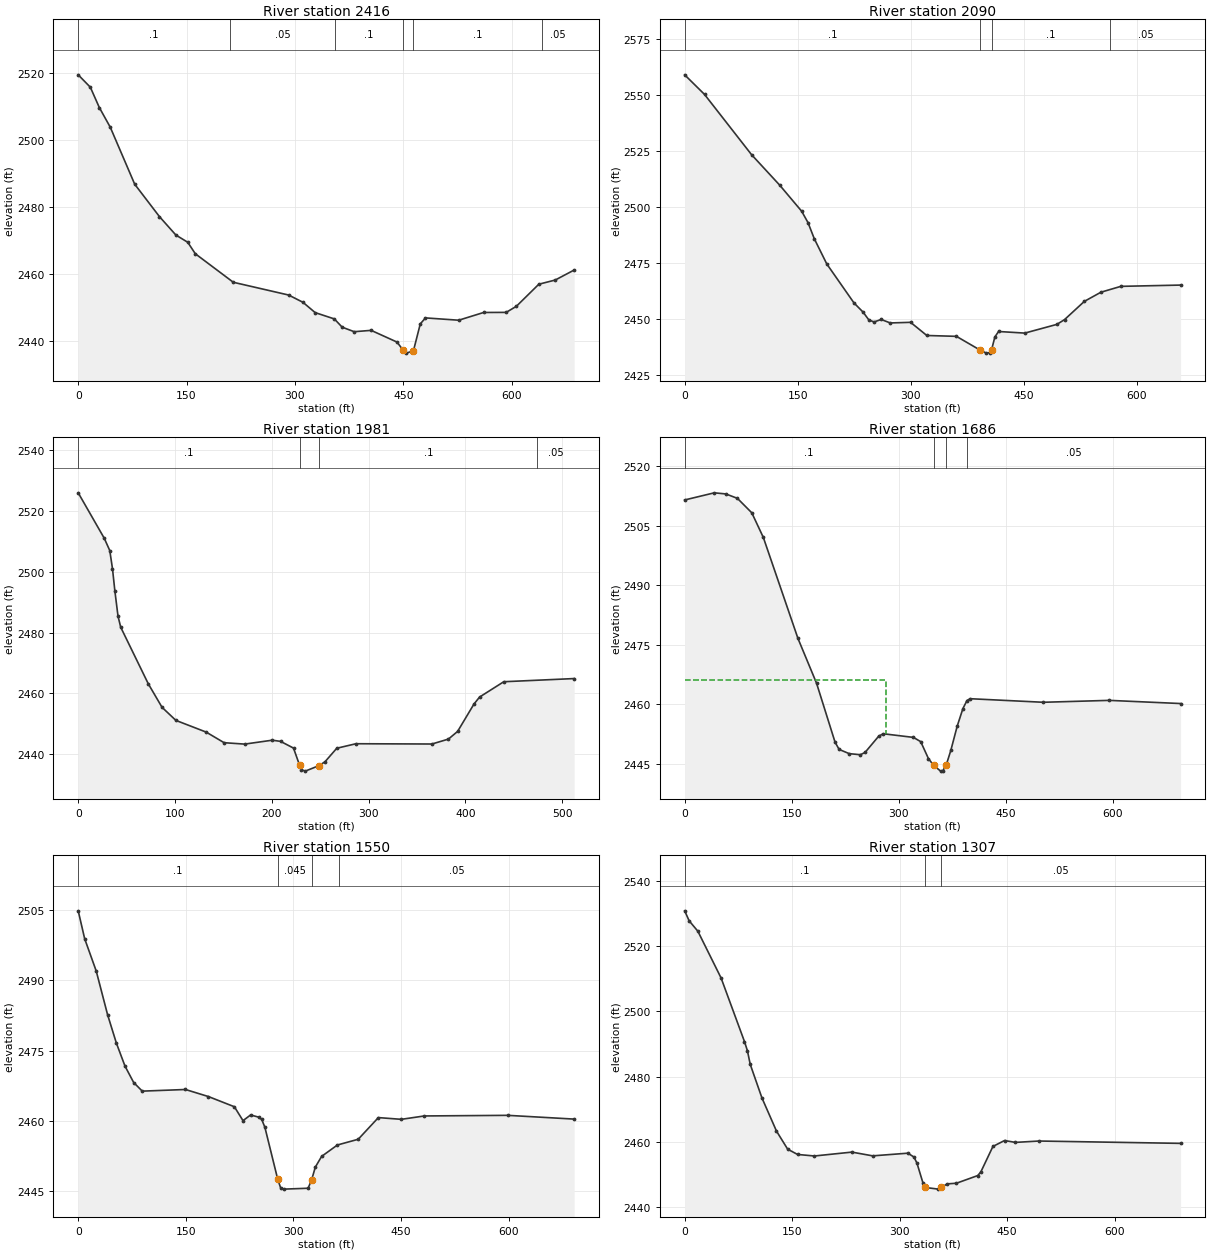
Type RM Length L Ch R = 1 ,2416    ,327.6,326.5,319.4
XS GIS Cut Line= 5
2175895.91157341410284.0449308032175700.75007638410118.924216223
2175558.27066915409987.2037508332175548.20329791 409967.06900835
2175394.05970492409818.201949174
#Sta/Elev= 30
       0 2519.51    16.8  2515.8    29.2 2509.75    44.4 2503.85    78.2 2486.84
   112.5 2477.15   135.2 2471.66   151.6  2469.5   162.1 2466.07   214.7 2457.55
   291.3 2453.74   311.1 2451.57     328 2448.49   354.5 2446.61   365.4 2444.14
     382 2442.79   405.5 2443.19   441.3 2439.69449.6798  2437.3   454.4 2436.39
464.07152437.118   473.5 2445.12   480.7 2446.91   526.7 2446.22   561.2 2448.53
   592.4 2448.56   606.5 2450.37   637.6 2456.97   660.3 2458.22   686.5 2461.21
#Mann= 6 ,-1,0
       0      .1       0     210     .05       0  355.64      .1       0
449.6798    .045       0464.0715      .1       0  642.19     .05       0
Bank Sta=449.6798,464.0715
XS Rating Curve= 0 ,0
Exp/Cntr(USF)=0,0
Exp/Cntr=0.3,0.1

Type RM Length L Ch R = 1 ,2090    ,115.9,108.1,97.5
XS GIS Cut Line= 3
2175997.42870032409935.9862099812175810.50196274409989.440964754
2175465.55090907409679.917316592
#Sta/Elev= 30
       0 2558.84    26.3 2550.12    88.7 2523.26   126.1 2509.65   155.2 2498.04
   163.6 2492.97   171.9 2485.82   188.5 2474.55   224.6 2457.17   236.7 2453.07
   244.4 2449.56   251.3  2448.7   260.7  2449.8   272.7 2448.25   299.7 2448.53
   321.2 2442.66   360.5 2442.28   391.7 2436.19   400.2  2434.8   404.4 2435.02
   407.1 2436.24   411.5 2442.02   416.4 2444.44   451.2 2443.73   493.7 2447.61
   503.9 2449.73   530.2 2457.87   552.2 2461.95   578.6 2464.56   657.9 2465.13
#Mann= 4 ,-1,0
       0      .1       0   391.7    .045       0   407.1      .1       0
  564.42     .05       0
Bank Sta=391.7,407.1
XS Rating Curve= 0 ,0
Exp/Cntr(USF)=0,0
Exp/Cntr=0.3,0.1

Type RM Length L Ch R = 1 ,1981    ,286.3,295.3,299.9
XS GIS Cut Line= 4
2175929.76560888409941.3616702452175756.57854883409802.475774458
2175715.14903755409794.1898722022175507.31098929409658.853468684
#Sta/Elev= 30
       0 2525.86    26.9 2510.95    32.6 2506.91    35.4 2500.98    37.9 2493.56
    41.1  2485.4    43.9 2481.75    72.4 2463.17    86.6 2455.46   100.9 2451.17
   132.2 2447.33   150.7 2443.85     172 2443.39   200.4 2444.67     209 2444.29
   222.4 2442.08   228.6 2436.52   230.6 2434.99   234.6 2434.52     249 2436.36
     255 2437.62   267.1 2442.03   286.9 2443.51   365.4 2443.42   382.4 2445.03
   391.9 2447.55   408.8 2456.53   414.6 2458.83   439.6 2463.86   512.3  2464.9
#Mann= 4 ,-1,0
       0      .1       0   228.6    .045       0     249      .1       0
  474.25     .05       0
Bank Sta=228.6,249
XS Rating Curve= 0 ,0
Exp/Cntr(USF)=0,0
Exp/Cntr=0.3,0.1

Type RM Length L Ch R = 1 ,1686    ,144.6,136.1,128.2
XS GIS Cut Line= 4
2176165.24272643409718.4495094672175982.01785149409691.305180981
  2175754.408987409509.6284662552175536.65871607409531.800182528
#Sta/Elev= 30
       0 2511.49    41.5 2513.29    57.7 2513.01    73.9  2511.9    94.1 2508.25
   110.3 2502.02   158.8 2476.56   184.9 2465.25   210.8  2450.4   216.5 2448.56
   230.7 2447.49   246.3 2447.22   252.8 2447.78     272 2451.89   278.4 2452.51
   320.7 2451.59   330.9 2450.52   341.7 2446.26   348.9 2444.56   358.8 2443.08
   361.8 2443.15   366.7 2444.63   373.1 2448.29   382.1 2454.44   390.1 2458.87
   395.8 2460.89   400.2 2461.35   502.8 2460.45   595.3 2460.93   695.3 2460.13
#Mann= 4 ,-1,0
       0      .1       0   348.9    .045       0   366.7      .1       0
  395.22     .05       0
#XS Ineff= 2 , 0
          281.58 2466.03
Permanent Ineff=
       F       F
Bank Sta=348.9,366.7
XS Rating Curve= 0 ,0
Exp/Cntr(USF)=0,0
Exp/Cntr=0.3,0.1

Type RM Length L Ch R = 1 ,1550    ,260.9,242.7,224.5
XS GIS Cut Line= 4
2176233.19704811409493.8687634142176000.69119233409512.103290481
 2175873.8983726409454.3006814872175555.72560937409473.150982413
#Sta/Elev= 30
       0 2504.83       9 2498.88    25.1    2492      41 2482.65    53.2 2476.63
    65.2 2471.73    77.3 2468.23    89.3 2466.39   149.5 2466.74   181.6 2465.23
   217.7 2463.06   229.7  2460.1   240.3 2461.31   251.4 2460.85   255.8 2460.35
   260.2 2458.69   278.1  2447.6   282.1  2445.8   286.5  2445.5   320.4 2445.69
   325.3 2447.43   330.5 2450.19   339.3 2452.48   361.3 2454.91   390.3 2456.13
   418.4 2460.75   450.4 2460.38   482.5  2461.1   598.7 2461.23   691.3 2460.43
#Mann= 4 ,-1,0
       0      .1       0   278.1    .045       0   325.3      .1       0
  363.22     .05       0
Bank Sta=278.1,325.3
XS Rating Curve= 0 ,0
Exp/Cntr(USF)=0,0
Exp/Cntr=0.3,0.1

Type RM Length L Ch R = 1 ,1307    ,205.7,227.4,256.6
XS GIS Cut Line= 4
2176270.26003221409290.0728382032175972.07475737409236.282553328
2175849.29258537409279.5486520322175590.86534717409265.516403804
#Sta/Elev= 30
       0 2530.87     6.2 2527.82    18.4 2524.61    50.8 2510.26    83.4 2490.77
    87.5 2487.97    91.5 2483.74   107.8 2473.46   128.1 2463.28   143.7 2457.73
   157.5 2456.11     181 2455.64   233.3 2456.83   262.3 2455.68   311.4  2456.5
   319.9 2455.32   324.1 2453.46   332.6 2447.29   335.92445.975   353.8 2445.47
     358 2445.97   366.3 2447.08   379.2 2447.28   408.9 2449.63   413.2 2450.73
   430.1 2458.57   446.3 2460.38   461.5 2459.81   494.4 2460.23     692 2459.51
#Mann= 3 ,-1,0
       0      .1       0   335.9    .045       0     358     .05       0
Bank Sta=335.9,358
XS Rating Curve= 0 ,0
Exp/Cntr(USF)=0,0
Exp/Cntr=0.3,0.1

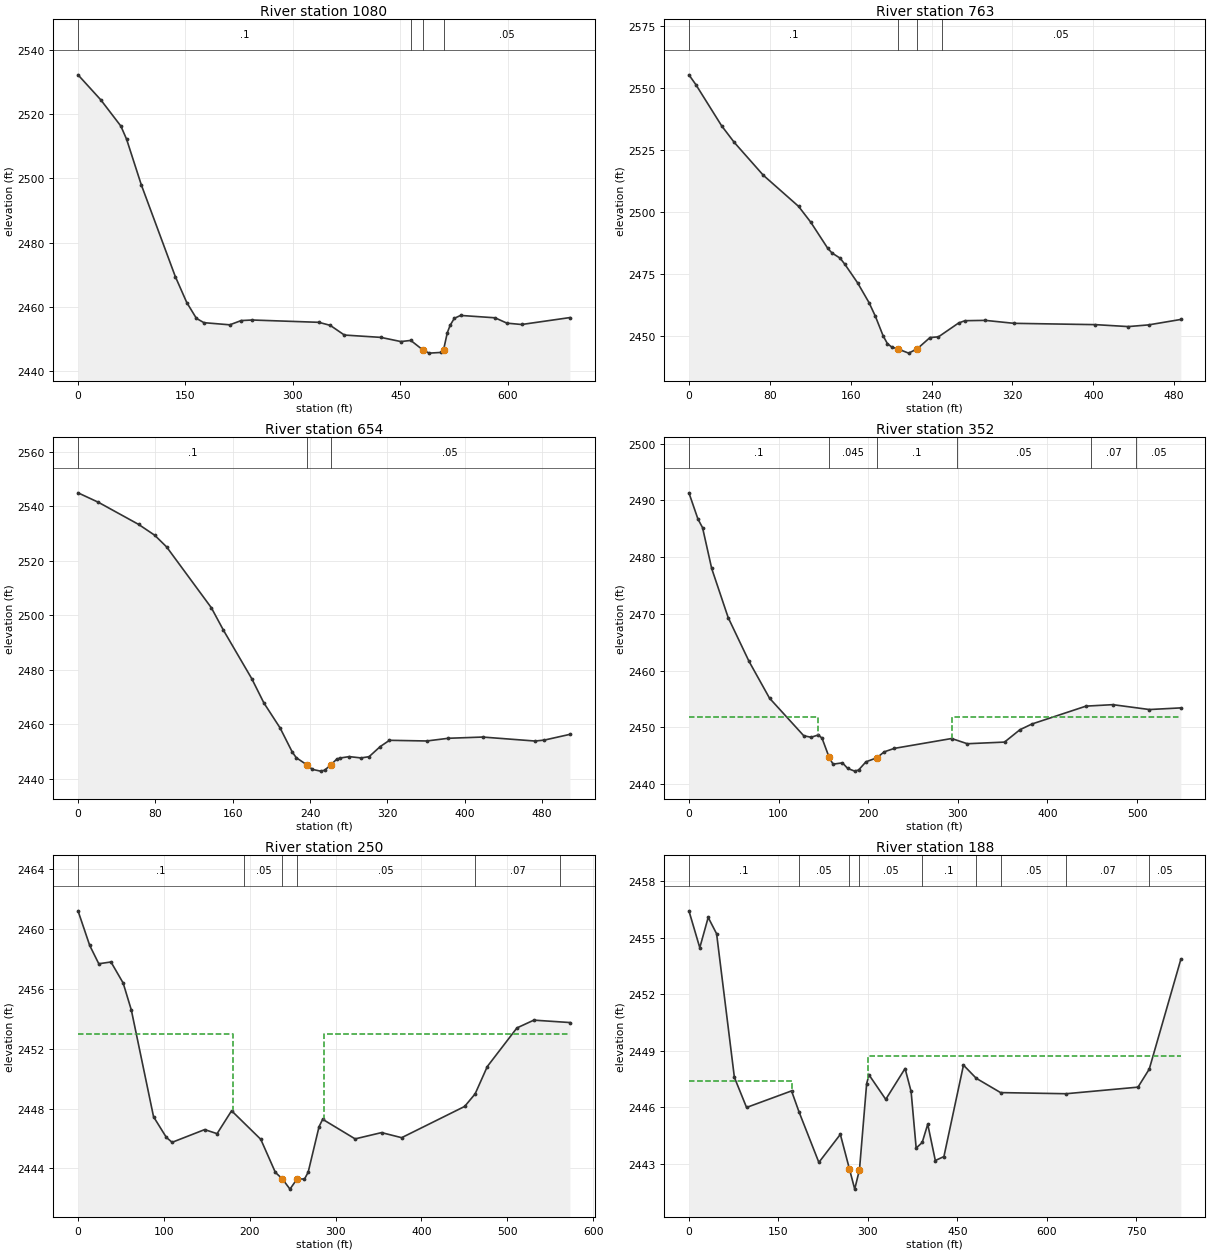
Type RM Length L Ch R = 1 ,1080    ,340.6,316.7,303.1
XS GIS Cut Line= 4
2176311.92461592409218.9438095262176016.91166284409211.343345368
2175884.70847994408985.7299776522175759.47069069408950.700926876
#Sta/Elev= 30
       0 2532.33    31.8 2524.52    59.8 2516.35    67.8 2512.25    88.3 2498.05
   135.8 2469.41   151.8  2461.3   165.3 2456.35   175.8 2455.02   211.8 2454.35
   227.8 2455.68   243.3 2455.85   336.1 2455.13     352 2454.19   371.8 2451.16
   422.8 2450.43   450.6 2449.13   464.5 2449.48   481.4 2446.51   490.2 2445.52
   506.2 2445.73   510.2 2446.51   515.5 2451.91   519.4 2454.18   525.2 2456.37
     534 2457.28   582.1 2456.54   598.7 2454.87   619.2 2454.45   686.6 2456.61
#Mann= 4 ,-1,0
       0      .1       0  465.11     .05       0   481.4    .045       0
   510.2     .05       0
Bank Sta=481.4,510.2
XS Rating Curve= 0 ,0
Exp/Cntr(USF)=0,0
Exp/Cntr=0.3,0.1

Type RM Length L Ch R = 1 ,763     ,108.4,108.8,109.2
XS GIS Cut Line= 3
 2176362.6037472408850.8046919032176081.95878264408943.183659404
2175892.52343156408918.627225005
#Sta/Elev= 30
       0 2555.17     6.8 2551.26    32.3 2534.67    44.7 2528.03    73.5 2514.76
   108.4 2502.22   120.5 2495.82   137.3 2485.31   141.5 2483.43   149.5 2481.35
   154.2  2478.9   166.8 2471.42   178.1 2463.46   184.4 2457.95   192.1 2450.04
   196.3 2446.93   200.5 2445.57   206.92444.744   217.3  2443.1   225.7  2444.8
   238.4 2449.37   246.8 2449.66   266.8 2455.25   273.1 2456.16   293.1 2456.29
   321.5  2455.1   402.1 2454.57   434.5 2453.79   454.6 2454.47   486.5 2456.66
#Mann= 4 ,-1,0
       0      .1       0   206.9    .045       0   225.7      .1       0
     250     .05       0
Bank Sta=206.9,225.7
XS Rating Curve= 0 ,0
Exp/Cntr(USF)=0,0
Exp/Cntr=0.3,0.1

Type RM Length L Ch R = 1 ,654     ,298,302.8,286.5
XS GIS Cut Line= 2
2176359.98986784408742.6420243062175873.53636993408891.602869705
#Sta/Elev= 30
       0 2544.86    21.1 2541.39    62.7 2533.28    79.3 2529.32    91.6 2525.05
   137.9 2502.73   150.4  2494.5   179.7 2476.73   192.2 2467.86     209 2458.67
   221.5 2449.89   225.7 2447.77   237.1 2445.06   242.4 2443.49   250.8 2442.85
     255 2443.17   261.3 2445.11   267.5 2447.23   270.9 2447.65   280.5 2448.17
   292.6 2447.69     301 2448.14   312.5 2451.84   322.1 2454.15   360.6  2453.9
     383 2454.89   418.5 2455.34   472.7 2453.88   482.3 2454.23   508.7 2456.33
#Mann= 3 ,-1,0
       0      .1       0   237.1    .045       0   261.3     .05       0
Bank Sta=237.1,261.3
XS Rating Curve= 0 ,0
Exp/Cntr(USF)=0,0
Exp/Cntr=0.3,0.1

Type RM Length L Ch R = 1 ,352     ,109.4,102.2,86.4
XS GIS Cut Line= 4
2176304.05185914408634.9095630992176233.61140373408578.971554396
2176038.73276745408617.8521789372175865.68295796408812.042361955
#Sta/Elev= 30
       0 2491.33    10.1 2486.69    15.2 2485.19    25.4 2477.99    43.8 2469.33
    67.1  2461.6    89.9 2455.13   128.1  2448.5   136.3 2448.23   144.4 2448.64
   148.5 2448.07156.4923 2444.67   160.8 2443.49   171.3 2443.72   177.1 2442.74
   184.9 2442.26   189.3 2442.46   197.5  2443.9209.5862 2444.61   217.9 2445.66
   229.1 2446.27   293.1 2448.01   310.6 2447.09   352.1 2447.38   369.3 2449.56
   382.7 2450.57     443 2453.72   472.9 2453.98   513.8 2453.12   548.8 2453.41
#Mann= 6 ,-1,0
       0      .1       0156.4923    .045       0209.5862      .1       0
  298.67     .05       0  448.67     .07       0  498.67     .05       0
#XS Ineff= 2 , 0
          143.88 2451.83  293.54         2451.73
Permanent Ineff=
       F       F
Bank Sta=156.4923,209.5862
XS Rating Curve= 0 ,0
Exp/Cntr(USF)=0,0
Exp/Cntr=0.3,0.1

Type RM Length L Ch R = 1 ,250     ,57.8,61.1,65.2
XS GIS Cut Line= 4
2176292.56340124408604.4909691222176154.58858434408516.507027915
2176033.61066518408559.4991810052175862.64187034408782.458486565
#Sta/Elev= 30
       0 2461.22    13.6 2458.91    24.2 2457.68    38.4  2457.8    52.6 2456.39
    62.1 2454.59      88 2447.45   102.9 2446.07   109.6 2445.74   147.5 2446.59
     162 2446.32   178.9 2447.85   212.9 2445.94   229.9 2443.73   238.1 2443.29
   246.9 2442.61   255.3  2443.3   263.8 2443.28   268.1 2443.74   280.8 2446.79
     285 2447.28   322.8 2445.97   353.6 2446.39     377 2446.05   450.4 2448.14
   462.6 2448.98   476.8 2450.81   511.3 2453.39     531 2453.91     573 2453.75
#Mann= 6 ,-1,0
       0      .1       0  193.64     .05       0   238.1    .045       0
   255.3     .05       0  462.03     .07       0  562.03     .05       0
#XS Ineff= 2 , 0
          180.51    2453  286.65            2453
Permanent Ineff=
       F       F
Bank Sta=238.1,255.3
XS Rating Curve= 0 ,0
Exp/Cntr(USF)=0,0
Exp/Cntr=0.3,0.1

Type RM Length L Ch R = 1 ,188     ,130.7,139.5,150.8
XS GIS Cut Line= 4
2176287.56978869408594.8262315382176140.01598879408502.651565609
2175953.43662469408497.8198290882175611.26606602408810.983018625
#Sta/Elev= 30
       0 2456.44    18.2 2454.48    32.3 2456.09    46.4 2455.22    76.2 2447.59
    96.6 2445.99     172 2446.87   184.6 2445.75   217.8 2443.07   253.8 2444.56
   268.92442.739   277.9 2441.65   285.9 2442.69   297.9 2447.26   301.9 2447.72
   329.9 2446.42   362.3 2448.06   372.4 2446.84   380.9 2443.83     391 2444.13
   400.3  2445.1     413 2443.17   427.4 2443.38   460.2 2448.24   481.6 2447.54
   522.4 2446.78   632.2 2446.72   752.7 2447.07   771.6 2448.03   824.5 2453.86
#Mann= 9 ,-1,0
       0      .1       0   184.6     .05       0   268.9    .045       0
   285.9     .05       0     391      .1       0   481.6     .07       0
   522.4     .05       0   632.2     .07       0   771.6     .05       0
#XS Ineff= 2 , 0
          172.39 2447.41     300         2448.72
Permanent Ineff=
       F       F
Bank Sta=268.9,285.9
XS Rating Curve= 0 ,0
Exp/Cntr(USF)=0,0
Exp/Cntr=0.3,0.1

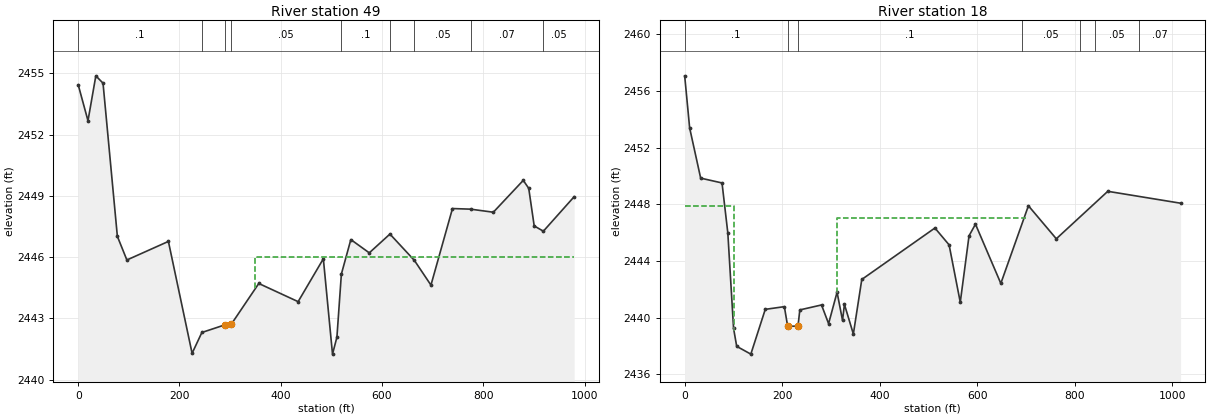
Type RM Length L Ch R = 1 ,49      ,30.8,31.1,31.9
XS GIS Cut Line= 5
2176289.74893796408591.4062127392176150.65270888408504.762472283
2176069.83702272408346.2393955742175887.61319189408442.985096801
2175599.55091211408763.922837759
#Sta/Elev= 30
       0 2454.44    19.3 2452.68    34.8 2454.88      49 2454.52    77.3 2447.02
    96.1 2445.86   178.1 2446.77   224.9 2441.29   244.2 2442.31     2892442.678
   302.2 2442.71   356.6 2444.71   434.3 2443.82   484.1 2445.92   502.2 2441.25
   510.9 2442.08   519.7 2445.17   538.4 2446.86   574.8 2446.21   615.6 2447.13
   663.9 2445.84   696.6 2444.63   739.1 2448.38   774.8 2448.35   819.8  2448.2
   878.9 2449.76   889.7 2449.37   900.5 2447.53   918.6 2447.27   979.4 2448.96
#Mann= 9 ,-1,0
       0      .1       0   244.2     .05       0     289    .045       0
   302.2     .05       0   519.7      .1       0   615.6     .07       0
   663.9     .05       0   774.8     .07       0   918.6     .05       0
#XS Ineff= 2 , 0
                             350            2446
Permanent Ineff=
       F       F
Bank Sta=289,302.2
XS Rating Curve= 0 ,0
Exp/Cntr(USF)=0,0
Exp/Cntr=0.3,0.1

Type RM Length L Ch R = 1 ,18      ,,,
XS GIS Cut Line= 5
2176304.05185914408599.6893353972176138.30961113408419.444640685
2176107.23293962408346.9324071812176046.42745306408298.977656491
2175572.44639801408692.654009097
#Sta/Elev= 30
       0 2457.06    10.2 2453.38    32.8 2449.84    76.6  2449.5    88.5 2445.97
   100.3 2439.23   106.7 2437.97   135.7 2437.42   165.3 2440.58   204.5 2440.77
   211.2 2439.39  232.432439.392   236.2 2440.54   280.7 2440.89   295.2 2439.57
   312.6 2441.79   323.8  2439.8   327.7 2440.93     346 2438.84   363.3 2442.69
   513.3 2446.32   542.4 2445.13   565.3 2441.08   583.3 2445.77   596.5 2446.59
   648.5 2442.41   705.1 2447.89   762.3 2445.56   867.9 2448.91  1017.3 2448.07
#Mann= 7 ,-1,0
       0      .1       0   211.2    .045       0  232.43      .1       0
   691.2     .05       0   811.2     .07       0   841.2     .05       0
   931.2     .07       0
#XS Ineff= 2 ,-1
       0  101.38 2447.87  312.39     700    2447
Permanent Ineff=
       F       F
Bank Sta=211.2,232.43
XS Rating Curve= 0 ,0
Exp/Cntr(USF)=0,0
Exp/Cntr=0.3,0.1
LCMann Table=0

Chan Stop Cuts=-1
Use User Specified Reach Order=0
Composite Channel Slope=5